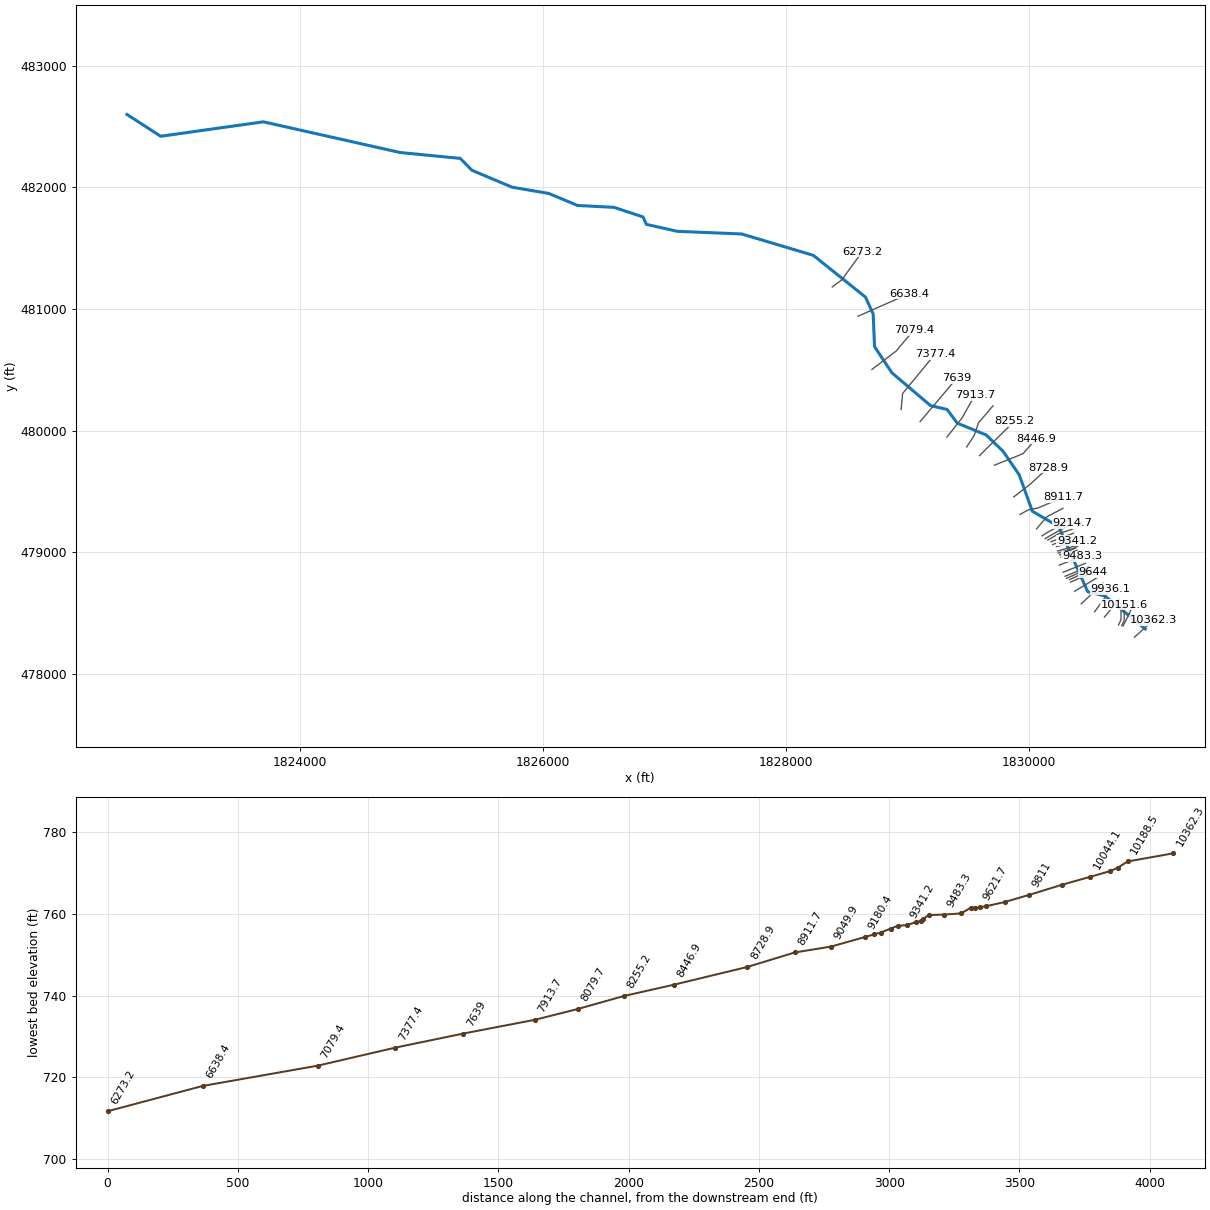
--- PTLCKFK.prj (project) ---

Proj Title=PTLCKFK
Current Plan=p01
Default Exp/Contr=0,0
English Units
Geom File=g01
Flow File=f01
Plan File=p01
BEGIN DESCRIPTION:
END DESCRIPTION:
DSS Export Rating Curves= 0
DSS Export Rating Curve Sorted= 0
DSS Export Volume Flow Curves= 0
DXF OffsetX= 0
DXF OffsetY= 0
DXF ScaleX= 0
DXF ScaleY= 0

--- PTLCKFK.p01 (plan) ---

Plan Title=Floodplain
Program Version=4.00
Geom File=g01
Flow File=f01
K Sum by GR=0
Std Step Tol=0.01
Critical Tol=0.01
Num of Std Step Trials=20
Max Error Tol=0.3
Flow Tol Ratio=0.001
Split Flow NTrial=30
Split Flow Tol=0.02
Split Flow Ratio=0.02
Log Output Level=0
Friction Slope Method=1
Unsteady Friction Slope Method=2
Unsteady Bridges Friction Slope Method=1
Global Log Level=0
CheckData=False
Run HTab=0
Run UNet=0
Run PostProcess=0
UNET Theta=0
UNET Theta Warmup=0
UNET ZTol=0
UNET ZSATol=0
UNET MxIter=0
UNET MaxInSteps=0
UNET DtIC=0
UNET DtMin=0
UNET MaxCRTS=0
UNET WFStab=0
UNET SFStab=0
UNET WFX=0
UNET SFX=0
UNET DSS MLevel=0
UNET DZMax Abort=0
UNET Convert EG Bridges=0
UNET Use Existing IB Tables=0
UNET Froude Limit=0
UNET Froude Power=0
Write IC File=0
Echo Input=False
Echo Output=False
Write Detailed=0

--- PTLCKFK.f01 (steady flow) ---

Flow Title=NFF Regression Equation
Program Version=4.10
Number of Profiles= 1
Profile Names=P100yr
River Rch & RM=PTLCKFK,Main            ,10362.3
865.4843
River Rch & RM=PTLCKFK,Main            ,8255.2
959.3076
River Rch & RM=PTLCKFK,Main            ,6638.4
1057.031
River Rch & RM=PTLCKFK,Main            ,5641.7
1143.386
River Rch & RM=PTLCKFK,Main            ,4248.3
1223.218
Boundary for River Rch & Prof#=PTLCKFK,Main            , 1
Up Type= 0
Dn Type= 3
Dn Slope=0.011
DSS Import GetInterval= 0
DSS Import GetPeak= 0
DSS Import FillOption= 0

--- PTLCKFK.g01 (geometry) ---

Geom Title=USGS 10m DEM
Program Version=4.10

River Reach=PTLCKFK         ,Main
Reach XY= 30
     1830957.333      478369.347     1830624.868      478640.181
     1830483.375      478675.771     1830244.731      479211.037
     1830028.104      479336.771     1829919.606      479636.759
     1829787.557      479829.395     1829648.306      479963.965
     1829410.458      480061.188     1829326.257      480174.035
     1829190.578      480205.035     1828872.264       480475.25
     1828729.503      480690.203      1828718.33      480957.814
     1828654.789      481097.397     1828225.969        481440.8
     1827636.066      481616.483     1827105.898      481638.302
     1826852.078      481695.586     1826824.134      481756.596
     1826586.587      481835.233     1826285.513      481850.818
      1826048.24      481949.875     1825747.637      482000.876
     1825416.039      482140.199     1825320.553      482237.855
     1824826.196      482286.032     1823700.602       482538.55
     1822855.338      482419.806     1822578.146      482598.808

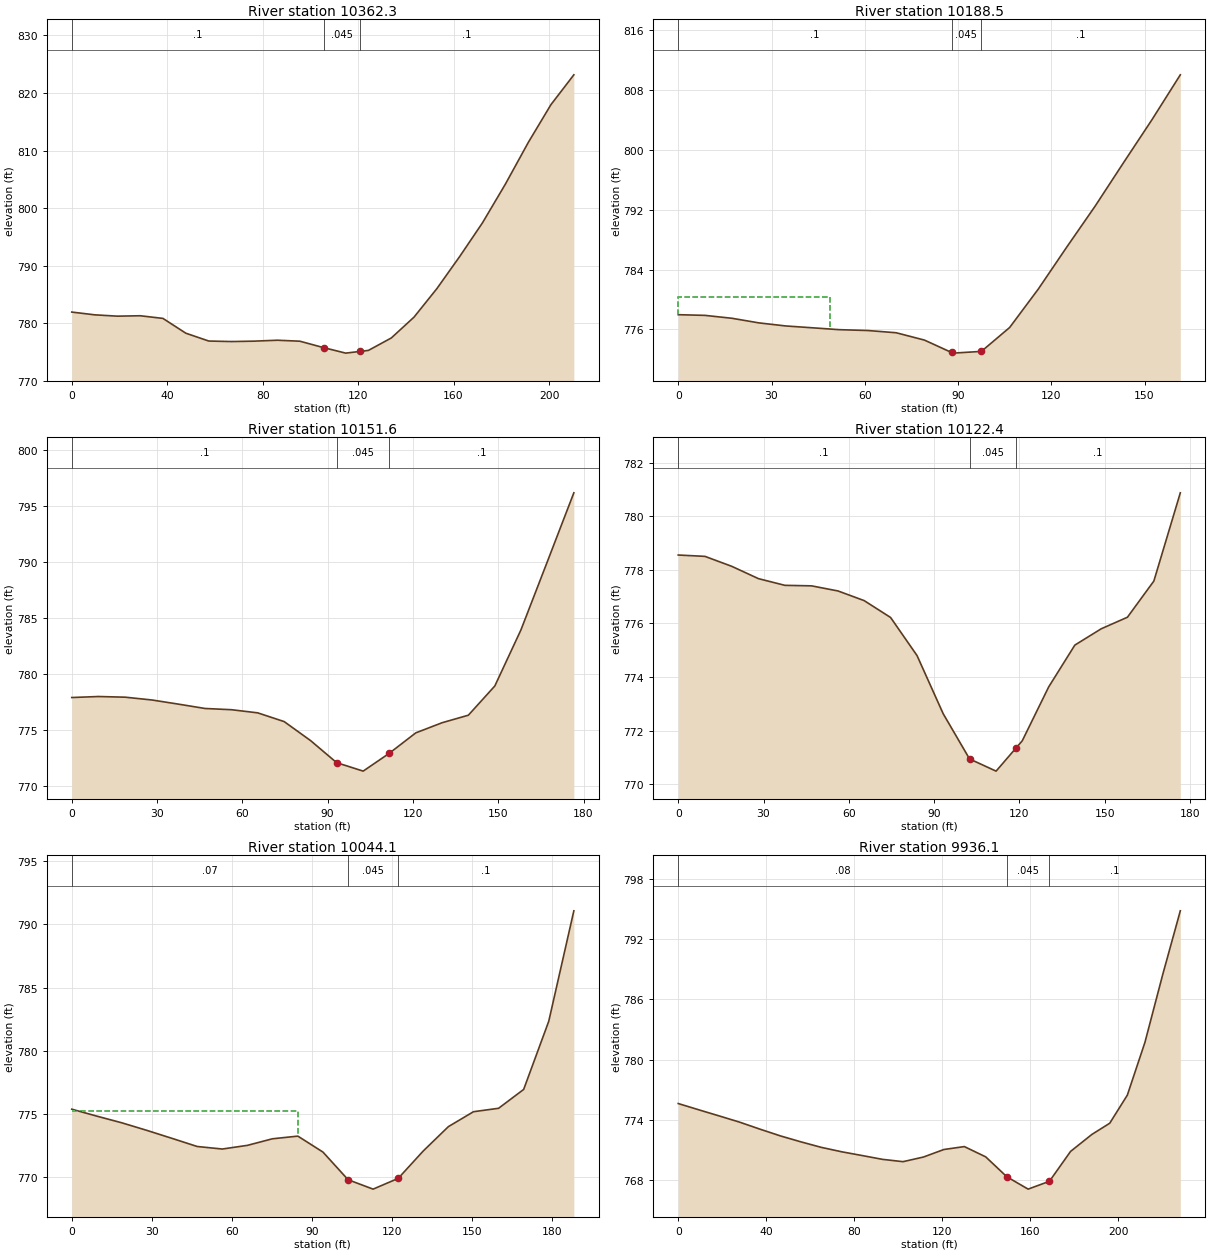
Type RM Length L Ch R = 1 ,10362.3 ,164.8,173.8,182.6
XS GIS Cut Line= 2
     1830867.961      478301.157     1831024.546      478441.662
#Sta/Elev= 25
       0  781.95     9.6  781.47    19.1  781.24    28.7  781.31    38.2  780.85
    47.8  778.28    57.4  776.92    66.9  776.83    76.5   776.9    86.1  777.06
    95.6  776.89   105.2  775.81   105.7  775.76   114.8  774.82   120.7  775.11
   124.3  775.29   133.9  777.45   143.4  781.06     153  786.02   162.6  791.62
   172.1  797.44   181.7  804.16   191.3   811.4   200.8  817.97   210.4  823.15
#Mann= 3 , 0 , 0
       0      .1       0   105.7    .045       0   120.7      .1       0
Bank Sta=105.7,120.7
XS Rating Curve= 0 ,0
Exp/Cntr=0.3,0.1

Type RM Length L Ch R = 1 ,10188.5 ,25.6,36.9,47.2
XS GIS Cut Line= 3
     1830773.909      478392.972     1830797.525      478439.048
     1830844.921      478538.007
#Sta/Elev= 21
       0  777.97     8.6  777.88    17.3  777.49    25.9  776.88    34.5  776.47
    43.2  776.22    51.8  775.97    60.9  775.86    70.1  775.56    79.2  774.58
    87.9  772.93    88.4  772.84    97.5  773.07   102.9  774.96   106.6  776.26
   115.8  781.38   124.9  786.95   134.1  792.46   143.2  798.24   152.4  804.01
   161.5  809.99
#Mann= 3 , 0 , 0
       0      .1       0    87.9    .045       0    97.5      .1       0
#XS Ineff= 2 , 0
           48.82  780.33
Permanent Ineff=
       F       F
Bank Sta=87.9,97.5
XS Rating Curve= 0 ,0
Exp/Cntr=0.3,0.1

Type RM Length L Ch R = 1 ,10151.6 ,29.3,29.2,29.3
XS GIS Cut Line= 3
     1830763.262      478396.524     1830783.721      478438.759
     1830784.095      478568.399
#Sta/Elev= 21
       0  777.91     9.4     778    18.8  777.94    28.2  777.69    37.5  777.32
    46.9  776.93    56.2  776.82    65.4  776.54    74.7  775.76      84  774.06
    93.2  772.08    96.6  771.81   102.5  771.33   111.6  772.91     121  774.75
   130.3  775.66   139.5  776.33   148.8  778.94     158  783.96   167.3  790.07
   176.6  796.21
#Mann= 3 , 0 , 0
       0      .1       0    93.2    .045       0   111.6      .1       0
Bank Sta=93.2,111.6
XS Rating Curve= 0 ,0
Exp/Cntr=0.3,0.1

Type RM Length L Ch R = 1 ,10122.4 ,95.2,78.3,62.1
XS GIS Cut Line= 3
     1830737.097      478402.338     1830757.556      478444.574
     1830757.931      478574.213
#Sta/Elev= 22
       0  778.55     9.4   778.5    18.8  778.13    28.2  777.67    37.5  777.42
    46.9   777.4    56.2  777.21    65.4  776.85    74.7  776.22      84   774.8
    93.2  772.63   102.5  770.94   103.8  770.88   111.8  770.49   118.8  771.35
     121  771.62   130.3  773.63   139.5  775.19   148.8   775.8     158  776.23
   167.3  777.58   176.6  780.87
#Mann= 3 , 0 , 0
       0      .1       0   102.5    .045       0   118.8      .1       0
Bank Sta=102.5,118.8
XS Rating Curve= 0 ,0
Exp/Cntr=0.3,0.1

Type RM Length L Ch R = 1 ,10044.1 ,102.8,108,113
XS GIS Cut Line= 2
     1830620.963      478467.173     1830742.317      478610.923
#Sta/Elev= 23
       0  775.39     9.4  774.84    18.8  774.31    28.2  773.71    37.6  773.08
      47  772.44    56.4  772.24    65.8  772.53    75.2  773.05    84.7  773.26
    94.1     772   103.5  769.82   105.2  769.68   112.9  769.07   120.2  769.73
   122.3  769.92   131.7  772.09   141.1  774.01   150.5  775.19   159.9  775.46
   169.3  776.95   178.7  782.34   188.1  791.07
#Mann= 3 , 0 , 0
       0     .07       0   103.5    .045       0   122.3      .1       0
#XS Ineff= 2 , 0
            84.7  775.25
Permanent Ineff=
       F       F
Bank Sta=103.5,122.3
XS Rating Curve= 0 ,0
Exp/Cntr=0.3,0.1

Type RM Length L Ch R = 1 ,9936.1  ,132.9,125.2,117.1
XS GIS Cut Line= 4
     1830540.754      478510.923     1830617.317      478616.132
     1830643.879      478667.694     1830670.963      478697.382
#Sta/Elev= 28
       0  775.63     9.3  775.01    18.6   774.4    27.9  773.78    37.2  773.08
    46.5  772.41    55.8  771.82    65.1  771.27    74.4  770.83    83.6  770.46
    92.9  770.08   102.2  769.85   111.5  770.31   120.8  771.06   130.1  771.35
   139.8  770.33   146.7  768.91   149.4  768.35   159.1  767.12   161.7  767.33
   168.8   767.9   178.4  770.87   188.1  772.56   196.2  773.67   204.2  776.46
   212.2   781.7   220.3  788.45   228.3  794.79
#Mann= 3 , 0 , 0
       0     .08       0   149.4    .045       0   168.8      .1       0
Bank Sta=149.4,168.8
XS Rating Curve= 0 ,0
Exp/Cntr=0.3,0.1

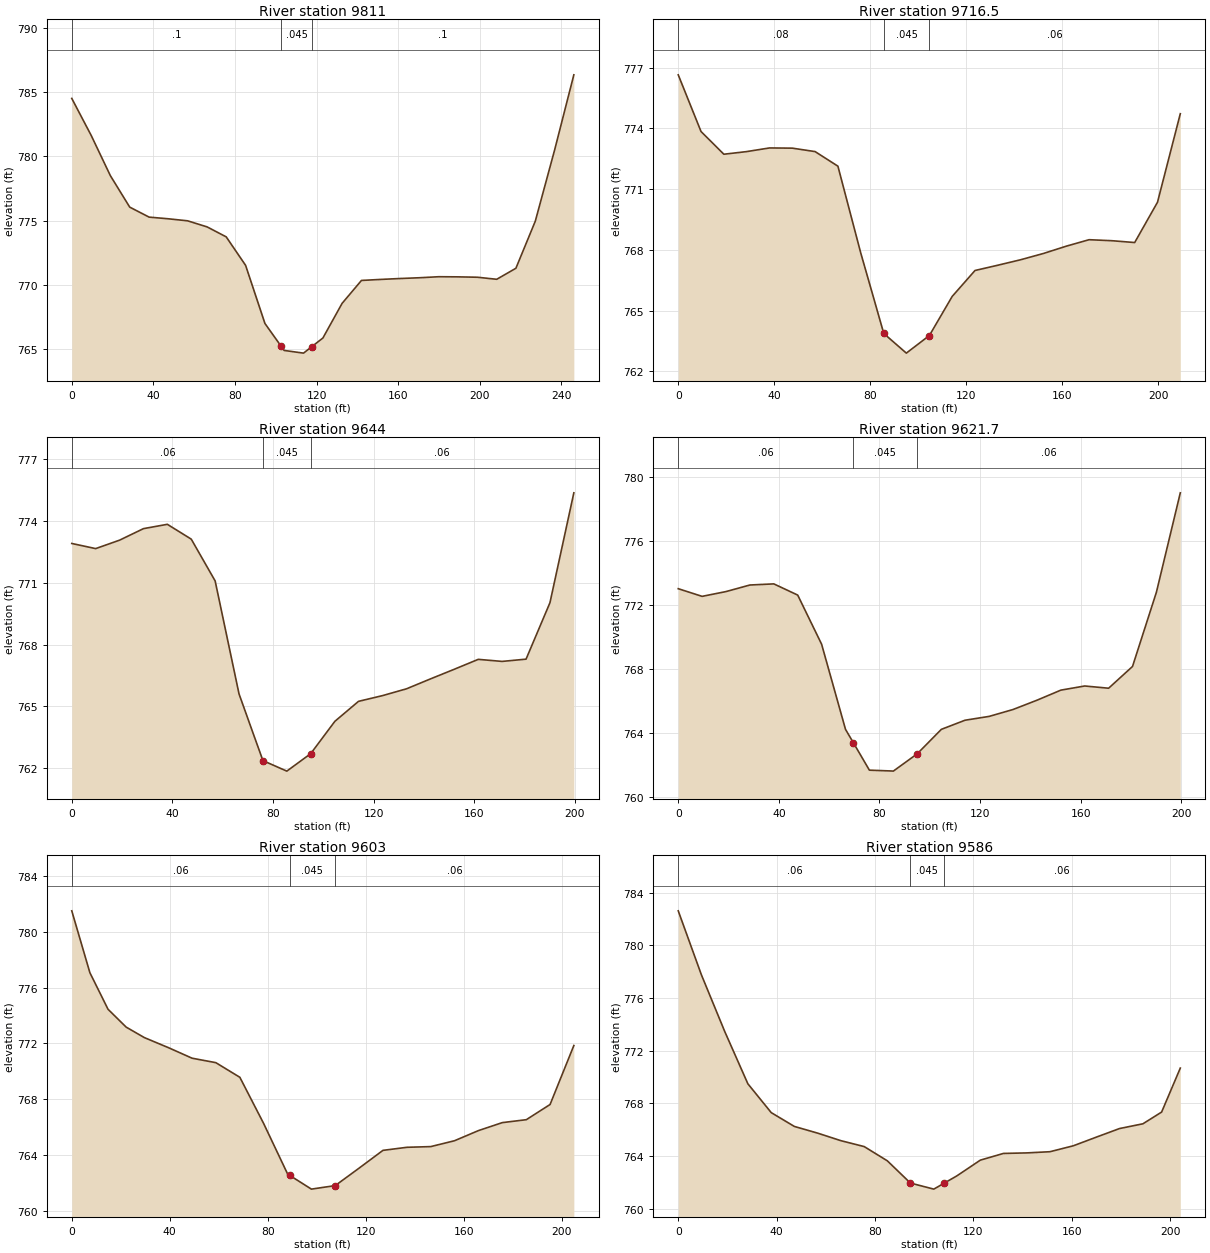
Type RM Length L Ch R = 1 ,9811    ,99.2,94.4,89.9
XS GIS Cut Line= 2
     1830430.338      478576.028     1830609.504      478744.778
#Sta/Elev= 29
       0  784.53     9.5  781.65    18.9  778.51    28.4  776.05    37.9  775.27
    47.3  775.14    56.8  774.98    66.3  774.51    75.7  773.73    85.2  771.51
    94.7  766.97   102.7  765.18   104.1  764.87   113.6  764.66   117.7  765.17
   123.1  765.84   132.5  768.54     142  770.33   151.5  770.41   160.9  770.48
   170.4  770.54   179.9  770.62   189.3  770.61   198.8  770.58   208.3  770.42
   217.7  771.28   227.2  774.95   236.7  780.52   246.1  786.37
#Mann= 3 , 0 , 0
       0      .1       0   102.7    .045       0   117.7      .1       0
Bank Sta=102.7,117.7
XS Rating Curve= 0 ,0
Exp/Cntr=0.3,0.1

Type RM Length L Ch R = 1 ,9716.5  ,75.2,72.5,69.9
XS GIS Cut Line= 2
     1830376.277      478678.843     1830555.223      478787.047
#Sta/Elev= 25
       0  776.64     9.5  773.84      19  772.72    28.5  772.85      38  773.03
    47.5  773.02      57  772.85    66.5  772.13      76  767.85    81.1  765.74
    85.6  763.87      95   762.9    96.1     763   104.6  763.77   114.1   765.7
   123.6  766.98   133.1  767.24   142.6  767.51   152.1  767.82   161.6  768.18
   171.1   768.5   180.6  768.45   190.1  768.36   199.6  770.35   209.1  774.72
#Mann= 3 , 0 , 0
       0     .08       0    85.6    .045       0   104.6     .06       0
Bank Sta=85.6,104.6
XS Rating Curve= 0 ,0
Exp/Cntr=0.3,0.1

Type RM Length L Ch R = 1 ,9644    ,22.3,22.3,22.4
XS GIS Cut Line= 2
     1830342.513      478753.925     1830524.175      478836.607
#Sta/Elev= 24
       0  772.92     9.5  772.67      19  773.08    28.5  773.64      38  773.85
    47.5  773.13      57   771.1    66.5  765.61    71.5   763.9      76  762.37
    85.5  761.86    86.5  761.95      95  762.71   104.6  764.28     114  765.25
   123.6  765.53   133.1  765.86   142.6  766.34   152.1  766.81   161.6  767.29
   171.1  767.19   180.6   767.3   190.1  770.04   199.6  775.38
#Mann= 3 , 0 , 0
       0     .06       0      76    .045       0      95     .06       0
Bank Sta=76,95
XS Rating Curve= 0 ,0
Exp/Cntr=0.3,0.1

Type RM Length L Ch R = 1 ,9621.7  ,18.9,18.6,18.3
XS GIS Cut Line= 2
      1830334.96      478774.993     1830516.622      478857.675
#Sta/Elev= 24
       0     773     9.5  772.52      19  772.82    28.5  773.23      38   773.3
    47.5   772.6      57  769.53    66.5  764.21    69.6  763.38      76  761.66
    84.6  761.61    85.5   761.6      95  762.68   104.6  764.21     114  764.78
   123.6  765.02   133.1  765.45   142.6  766.03   152.1  766.66   161.6  766.92
   171.1  766.78   180.6  768.14   190.1  772.78   199.6  778.99
#Mann= 3 , 0 , 0
       0     .06       0    69.6    .045       0      95     .06       0
Bank Sta=69.6,95
XS Rating Curve= 0 ,0
Exp/Cntr=0.3,0.1

Type RM Length L Ch R = 1 ,9603    ,17.8,17.1,16.3
XS GIS Cut Line= 3
     1830309.269       478785.76     1830336.579      478797.222
     1830497.144      478867.612
#Sta/Elev= 25
       0  781.51     7.4  777.07    14.8  774.45    22.2  773.17    29.6  772.42
    39.4   771.7    49.1  770.94    58.8  770.62    68.6  769.57    78.3  766.26
    88.1  762.63    88.9  762.54    97.8  761.55   103.9  761.71   107.5   761.8
   117.3  763.06     127  764.33   136.8  764.55   146.5   764.6   156.2  765.02
     166  765.75   175.7  766.32   185.5  766.53   195.2  767.62   204.9  771.85
#Mann= 3 , 0 , 0
       0     .06       0    88.9    .045       0   107.5     .06       0
Bank Sta=88.9,107.5
XS Rating Curve= 0 ,0
Exp/Cntr=0.3,0.1

Type RM Length L Ch R = 1 ,9586    ,36.9,36.9,36.9
XS GIS Cut Line= 3
     1830297.595      478802.421     1830473.033      478872.444
     1830487.394      478877.426
#Sta/Elev= 25
       0  782.61     9.4  777.76    18.9  773.45    28.3  769.48    37.8  767.29
    47.2  766.24    56.7  765.73    66.1  765.16    75.6  764.71      85  763.63
      93  762.19    94.4  761.94   103.9  761.48     108  761.92   113.3  762.49
   122.8  763.68   132.2  764.19   141.7  764.23   151.1  764.32   160.6  764.77
     170  765.43   179.4  766.08   188.9  766.44   196.5  767.33   204.1  770.67
#Mann= 3 , 0 , 0
       0     .06       0    94.4    .045       0     108     .06       0
Bank Sta=94.4,108
XS Rating Curve= 0 ,0
Exp/Cntr=0.3,0.1

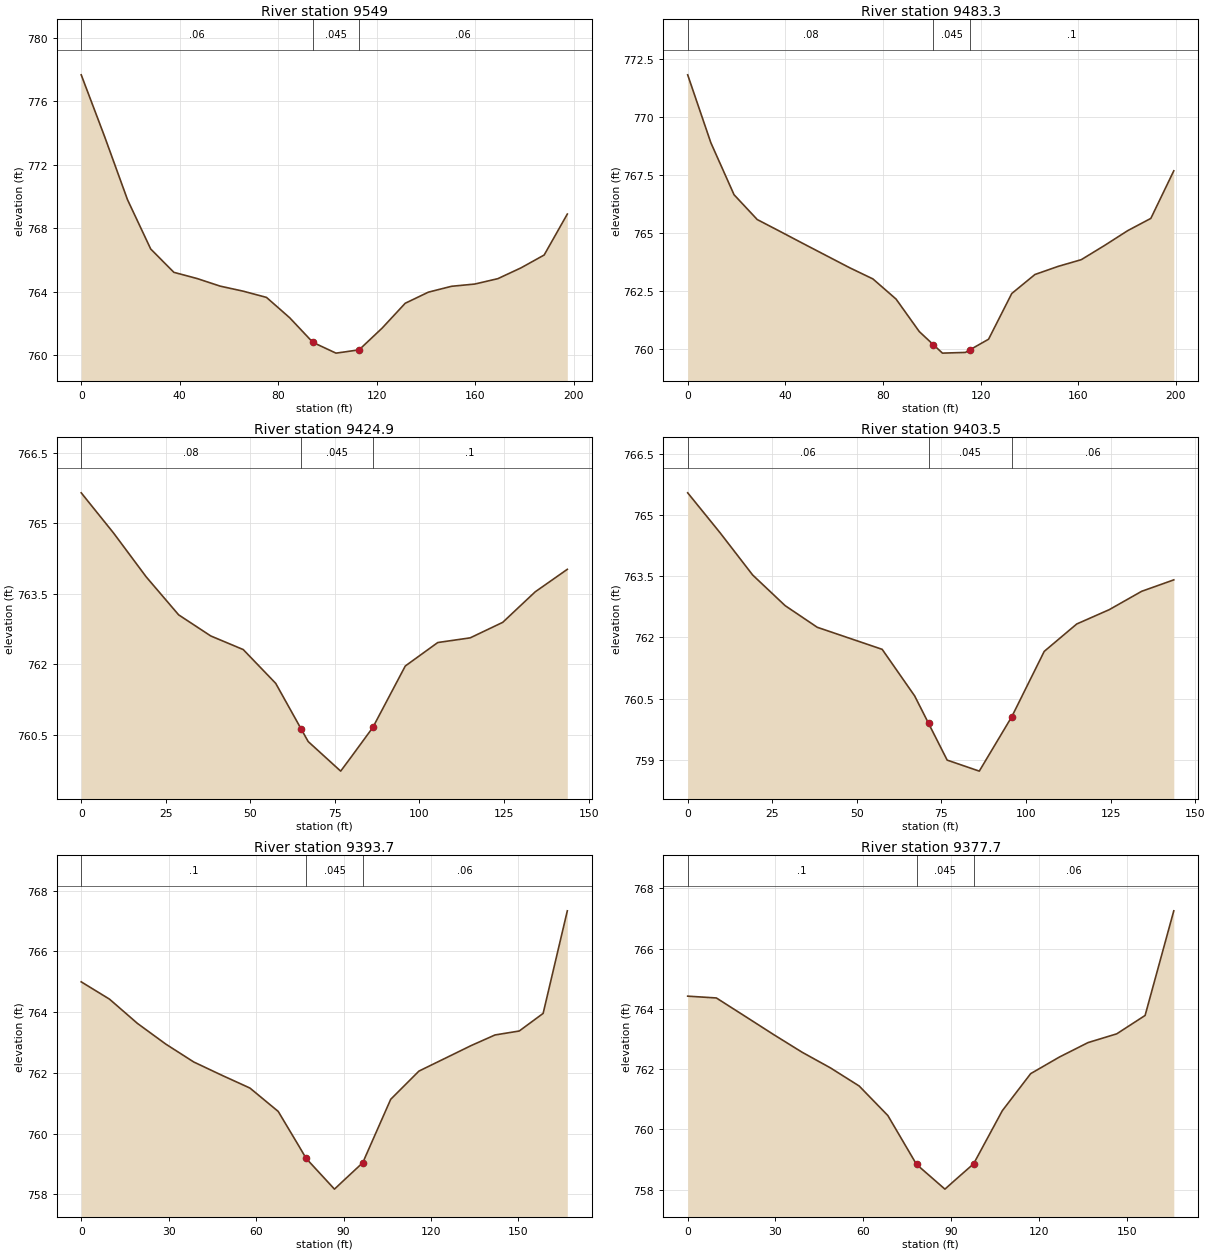
Type RM Length L Ch R = 1 ,9549    ,65.9,65.8,65.7
XS GIS Cut Line= 2
     1830281.297      478835.414     1830464.549      478908.556
#Sta/Elev= 24
       0  777.65     9.4   773.8    18.8  769.78    28.2  766.68    37.6  765.21
      47  764.82    56.4  764.34    65.8  764.02    75.2  763.63    84.6  762.35
    91.7  761.18      94   760.8   103.4  760.12   106.7  760.19   112.8  760.33
   122.1  761.69   131.5  763.26   140.9  763.96   150.3  764.33   159.7  764.47
   169.1  764.81   178.5  765.49   187.9   766.3   197.3  768.88
#Mann= 3 , 0 , 0
       0     .06       0      94    .045       0   112.8     .06       0
Bank Sta=94,112.8
XS Rating Curve= 0 ,0
Exp/Cntr=0.3,0.1

Type RM Length L Ch R = 1 ,9483.3  ,57.6,58.4,59
XS GIS Cut Line= 2
     1830249.894      478894.093      1830435.31       478967.01
#Sta/Elev= 24
       0  771.83     9.5   768.9      19  766.66    28.5  765.59      38  765.07
    47.4  764.55    56.9  764.03    66.4  763.51    75.9  763.03    85.4  762.16
    94.9  760.76   100.6   760.2   104.4  759.83   113.8  759.86   115.6  759.97
   123.3  760.43   132.8   762.4   142.3  763.22   151.8  763.57   161.3  763.86
   170.8  764.47   180.3  765.11   189.8  765.64   199.2  767.69
#Mann= 3 , 0 , 0
       0     .08       0   100.6    .045       0   115.6      .1       0
Bank Sta=100.6,115.6
XS Rating Curve= 0 ,0
Exp/Cntr=0.3,0.1

Type RM Length L Ch R = 1 ,9424.9  ,21.3,21.4,21.3
XS GIS Cut Line= 2
     1830263.409      478959.437     1830395.432      479016.269
#Sta/Elev= 18
       0  765.65     9.6  764.79    19.2  763.86    28.8  763.05    38.3   762.6
    47.9  762.31    57.5  761.59      65  760.62    67.1  760.35    76.7  759.72
      80  760.04    86.2  760.65    95.8  761.96   105.4  762.46     115  762.56
   124.6  762.89   134.2  763.54   143.7  764.02
#Mann= 3 , 0 , 0
       0     .08       0      65    .045       0    86.2      .1       0
Bank Sta=65,86.2
XS Rating Curve= 0 ,0
Exp/Cntr=0.3,0.1

Type RM Length L Ch R = 1 ,9403.5  ,12.5,9.8,7.1
XS GIS Cut Line= 2
     1830251.086      478977.325     1830383.109      479034.157
#Sta/Elev= 17
       0  765.54     9.6  764.56    19.2  763.53    28.8  762.78    38.3  762.25
    47.9  761.98    57.5  761.71    67.1  760.57    71.2   759.9    76.7     759
    86.2  758.73    95.8  760.06   105.4  761.66     115  762.33   124.6  762.68
   134.2  763.13   143.7  763.41
#Mann= 3 , 0 , 0
       0     .06       0    71.2    .045       0    95.8     .06       0
Bank Sta=71.2,95.8
XS Rating Curve= 0 ,0
Exp/Cntr=0.3,0.1

Type RM Length L Ch R = 1 ,9393.7  ,16,16,16
XS GIS Cut Line= 3
     1830240.989      478994.419     1830361.408      479029.873
      1830398.96      479046.889
#Sta/Elev= 21
       0     765     9.7  764.43    19.3  763.63      29  762.95    38.6  762.36
    48.3  761.92    57.9   761.5    67.6  760.73      75  759.54    77.2  759.18
    86.9  758.17      90  758.45    96.6  759.04   106.2  761.13   115.9  762.06
   125.5  762.51   133.8   762.9     142  763.25   150.3  763.38   158.5  763.96
   166.8  767.34
#Mann= 3 , 0 , 0
       0      .1       0    77.2    .045       0    96.6     .06       0
Bank Sta=77.2,96.6
XS Rating Curve= 0 ,0
Exp/Cntr=0.3,0.1

Type RM Length L Ch R = 1 ,9377.7  ,36.9,36.5,36.1
XS GIS Cut Line= 2
     1830235.822      479009.524     1830395.159      479056.436
#Sta/Elev= 20
       0  764.42     9.8  764.36    19.5  763.76    29.3  763.15    39.1  762.56
    48.8  762.04    58.6  761.44    68.4  760.46    75.9  759.22    78.2  758.84
    87.9  758.02    90.9  758.28    97.7  758.86   107.5  760.62   117.2  761.85
     127   762.4   136.8  762.88   146.6  763.17   156.3  763.78   166.1  767.25
#Mann= 3 , 0 , 0
       0      .1       0    78.2    .045       0    97.7     .06       0
Bank Sta=78.2,97.7
XS Rating Curve= 0 ,0
Exp/Cntr=0.3,0.1

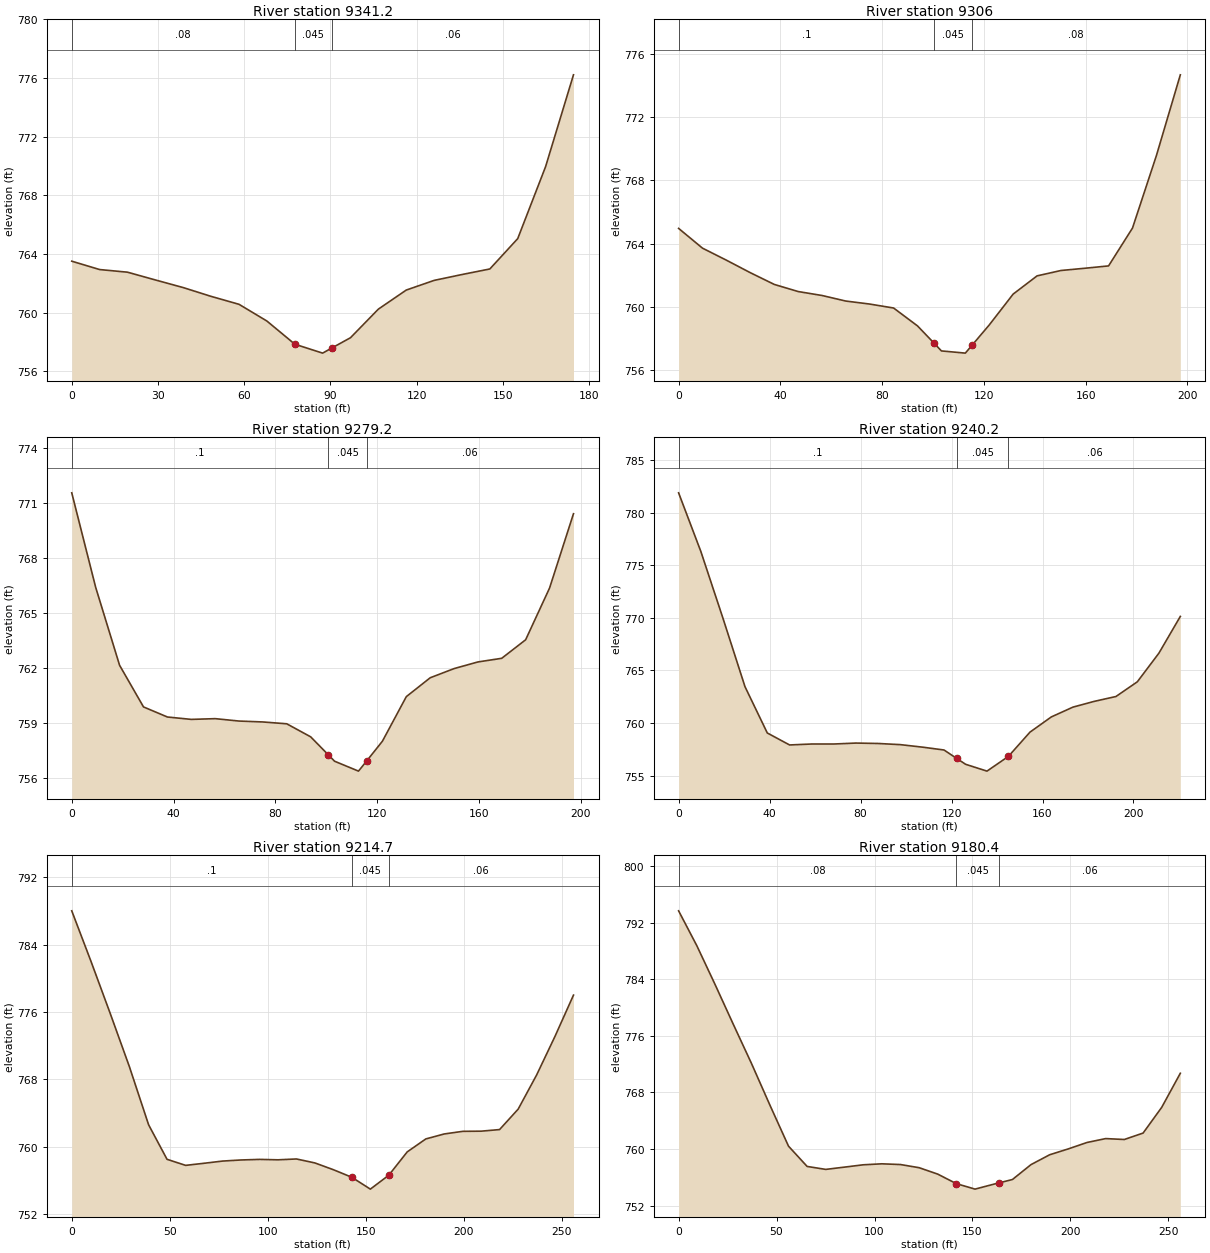
Type RM Length L Ch R = 1 ,9341.2  ,33,35.2,37.3
XS GIS Cut Line= 2
     1830227.434      479046.598     1830395.797      479092.983
#Sta/Elev= 21
       0  763.51     9.7  762.94    19.4  762.76    29.1  762.23    38.8  761.71
    48.5  761.11    58.2  760.57    67.9  759.43    75.6  758.18    77.6  757.85
    87.3  757.24    90.6   757.6      97  758.29   106.7  760.24   116.4  761.54
   126.1   762.2   135.8   762.6   145.5  762.98   155.2  765.05   164.9  769.96
   174.6  776.22
#Mann= 3 , 0 , 0
       0     .08       0    77.6    .045       0    90.6     .06       0
Bank Sta=77.6,90.6
XS Rating Curve= 0 ,0
Exp/Cntr=0.3,0.1

Type RM Length L Ch R = 1 ,9306    ,26.8,26.7,26.8
XS GIS Cut Line= 2
     1830195.656      479063.053     1830379.823      479133.595
#Sta/Elev= 24
       0  764.96     9.4  763.71    18.8  762.95    28.2  762.16    37.6  761.42
      47  760.97    56.4  760.72    65.7  760.37    75.1  760.18    84.5  759.93
    93.9   758.8   100.4  757.71   103.3  757.22   112.7  757.08   115.4  757.59
   122.1  758.86   131.5  760.81   140.9  761.96   150.3   762.3   159.6  762.44
     169  762.59   178.4  764.98   187.8  769.56   197.2  774.66
#Mann= 3 , 0 , 0
       0      .1       0   100.4    .045       0   115.4     .08       0
Bank Sta=100.4,115.4
XS Rating Curve= 0 ,0
Exp/Cntr=0.3,0.1

Type RM Length L Ch R = 1 ,9279.2  ,39.8,39.1,37.8
XS GIS Cut Line= 2
     1830181.453      479085.778      1830365.62       479156.32
#Sta/Elev= 24
       0  771.57     9.4  766.42    18.8  762.17    28.2   759.9    37.6  759.35
      47  759.22    56.4  759.26    65.7  759.13    75.1  759.08    84.5  758.98
    93.9  758.27   100.9  757.28   103.3  756.94   112.7   756.4   115.9  756.95
   122.1  758.03   131.5  760.46   140.9  761.49   150.3  761.99   159.6  762.35
     169  762.55   178.4  763.56   187.8  766.38   197.2  770.43
#Mann= 3 , 0 , 0
       0      .1       0   100.9    .045       0   115.9     .06       0
Bank Sta=100.9,115.9
XS Rating Curve= 0 ,0
Exp/Cntr=0.3,0.1

Type RM Length L Ch R = 1 ,9240.2  ,21.3,25.5,29.8
XS GIS Cut Line= 3
     1830155.281       479099.87     1830248.181      479153.482
     1830355.815      479189.087
#Sta/Elev= 26
       0   781.9     9.8  776.31    19.5  769.97    29.2  763.45      39  759.05
    48.8  757.91    58.5     758    68.3     758      78  758.09    87.8  758.05
    97.5  757.94   107.3   757.7   116.7  757.43   122.2  756.64   126.2  756.07
   135.6  755.42   137.2  755.66     145  756.82   154.5  759.13   163.9  760.58
   173.4  761.51   182.8  762.06   192.3  762.52   201.7  763.92   211.2  766.65
   220.6  770.14
#Mann= 3 , 0 , 0
       0      .1       0   122.2    .045       0     145     .06       0
Bank Sta=122.2,145
XS Rating Curve= 0 ,0
Exp/Cntr=0.3,0.1

Type RM Length L Ch R = 1 ,9214.7  ,35.1,34.3,34.1
XS GIS Cut Line= 3
     1830134.409      479111.329     1830167.545       479132.31
     1830356.838      479237.818
#Sta/Elev= 30
       0     788     9.8  782.01    19.6  775.83    29.4   769.5    39.2   762.6
    48.6   758.5    58.1  757.78    67.5  758.03    76.9  758.29    86.3  758.42
    95.8  758.49   105.2  758.44   114.6  758.54     124  758.07   133.4  757.27
   137.8  756.85   142.9  756.36   152.3  754.96   152.8  755.05   161.7  756.61
   171.1  759.38   180.6  760.92     190  761.51   199.4  761.82   208.8  761.84
   218.2  762.03   227.7  764.46   237.1  768.51   246.5  773.11   255.9  777.99
#Mann= 3 , 0 , 0
       0      .1       0   142.9    .045       0   161.7     .06       0
Bank Sta=142.9,161.7
XS Rating Curve= 0 ,0
Exp/Cntr=0.3,0.1

Type RM Length L Ch R = 1 ,9180.4  ,121,130.4,138.4
XS GIS Cut Line= 3
     1830107.399      479134.657     1830146.663      479159.663
     1830329.712       479261.69
#Sta/Elev= 30
       0   793.7     9.3  788.77    18.6  783.29    27.9  777.66    37.2  772.11
    46.6  766.22    56.1  760.41    65.6  757.54    75.1  757.12    84.6  757.44
    94.2  757.77   103.7  757.91   113.2  757.81   122.8  757.36   132.3  756.45
   141.8   755.1   148.4  754.57   151.3  754.33   160.9  755.03   163.4   755.2
   170.4  755.69   179.9   757.8   189.4  759.19     199  760.03   208.5  760.93
     218  761.48   227.5  761.35   237.1  762.26   246.6   765.9   256.1  770.72
#Mann= 3 , 0 , 0
       0     .08       0   141.8    .045       0   163.4     .06       0
Bank Sta=141.8,163.4
XS Rating Curve= 0 ,0
Exp/Cntr=0.3,0.1

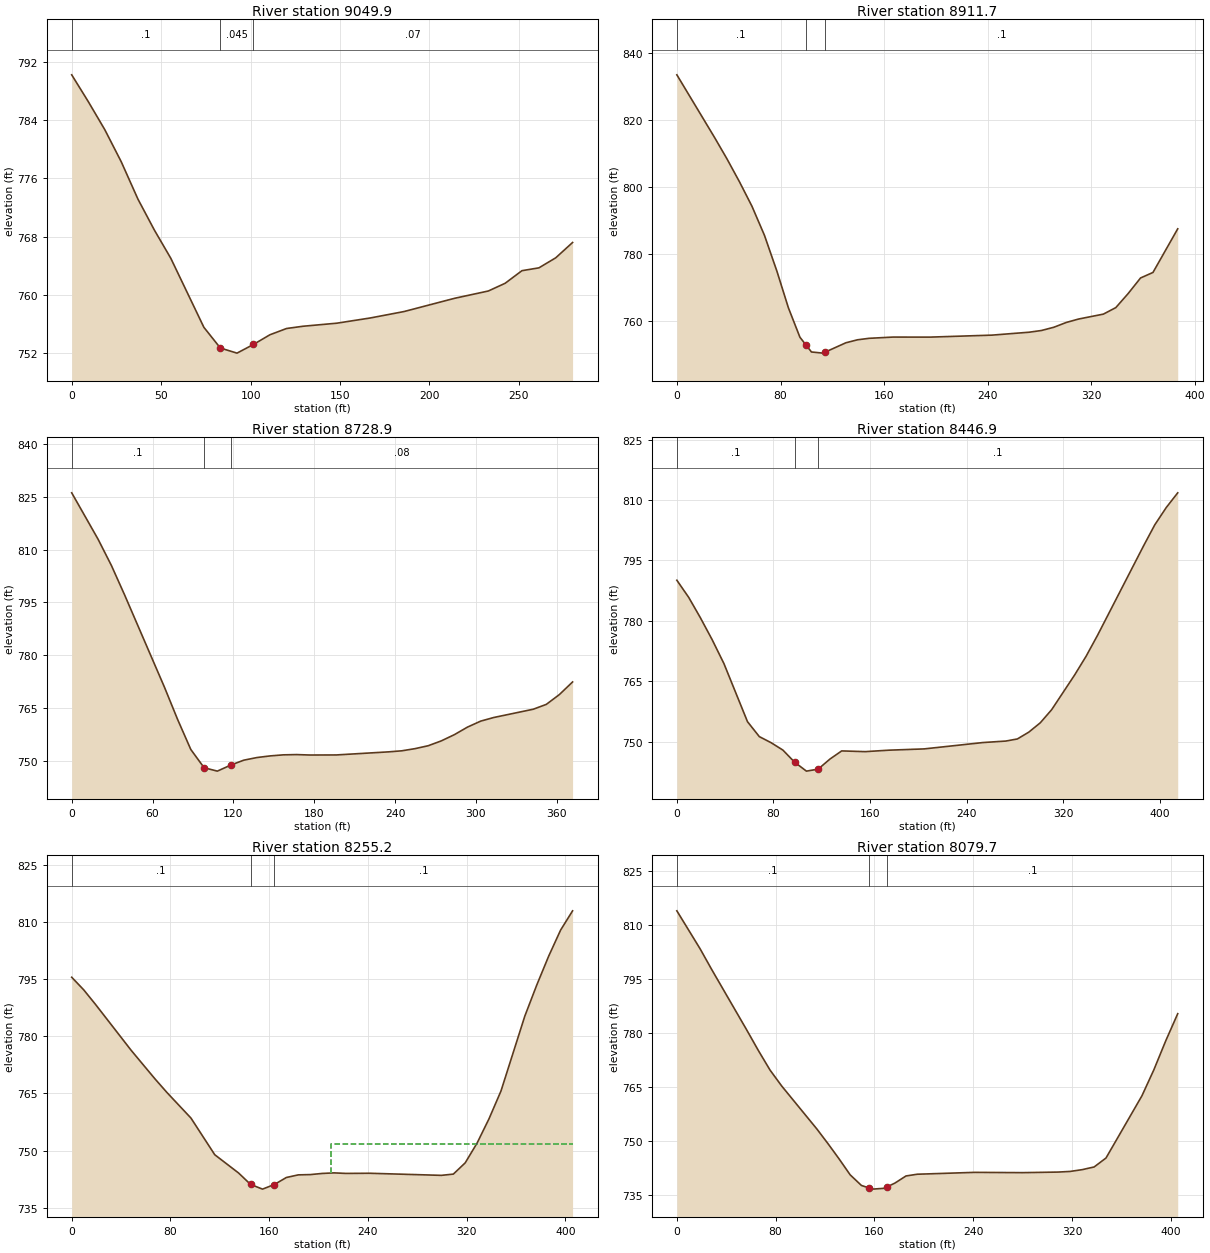
Type RM Length L Ch R = 1 ,9049.9  ,153.6,138.3,123
XS GIS Cut Line= 3
     1830062.592      479192.017      1830146.36      479290.541
     1830279.606      479360.854
#Sta/Elev= 24
       0   790.2     9.2  786.55    18.5  782.67    27.7  778.26      37  773.15
    46.2  768.89    55.4  765.01    73.9  755.53    83.1  752.69    92.4  751.99
   101.6  753.18   110.8  754.51   120.1  755.37   129.3  755.68   148.2   756.1
     167  756.82   185.8   757.7   214.1  759.52   232.9  760.52   242.3  761.58
   251.7  763.31   261.2   763.7   270.6  765.08     280  767.18
#Mann= 3 , 0 , 0
       0      .1       0    83.1    .045       0   101.6     .07       0
Bank Sta=83.1,101.6
XS Rating Curve= 0 ,0
Exp/Cntr=0.3,0.1

Type RM Length L Ch R = 1 ,8911.7  ,172.1,182.8,193.5
XS GIS Cut Line= 4
     1829926.539      479310.547     1829994.312      479347.641
     1830072.676      479363.224      1830284.07      479452.372
#Sta/Elev= 30
       0  833.48      29  814.88    38.6   808.5    48.3  801.63    57.9  794.38
    67.6  785.68    77.3  774.89    86.1  764.06      95  755.29    99.4  753.12
   103.9   750.9   112.8  750.56   114.4  750.85   130.5  753.65   139.4  754.53
   148.3  754.97   166.7  755.34   195.4  755.33   243.2  755.92   271.9  756.79
   281.4   757.3     291  758.27   300.6   759.7   310.1  760.72   329.2  762.18
   338.8  764.12   348.3  768.29   357.9  772.95   367.5   774.6   386.6   787.6
#Mann= 3 , 0 , 0
       0      .1       0    99.4    .045       0   114.4      .1       0
Bank Sta=99.4,114.4
XS Rating Curve= 0 ,0
Exp/Cntr=0.3,0.1

Type RM Length L Ch R = 1 ,8728.9  ,287.9,281.9,275.3
XS GIS Cut Line= 3
     1829874.923      479454.541     1830014.762      479562.834
     1830157.898      479695.141
#Sta/Elev= 30
       0  826.14    19.6  812.93    29.5  805.45    39.3  797.08    68.8  770.91
    78.6  761.71    88.4  753.16    98.3  747.96   108.1     747   117.9  748.69
   127.7  750.11   137.6  750.87   147.4  751.33   157.2  751.63     167   751.7
   176.9  751.58   196.4   751.6   235.3  752.48   245.1  752.78   254.8  753.39
   264.6  754.22   274.3  755.59   284.1  757.38   293.8  759.52   303.6  761.22
   313.3  762.25   342.6   764.6   352.3  765.98     362  768.77   371.8  772.36
#Mann= 3 , 0 , 0
       0      .1       0    98.3    .045       0   117.9     .08       0
Bank Sta=98.3,117.9
XS Rating Curve= 0 ,0
Exp/Cntr=0.3,0.1

Type RM Length L Ch R = 1 ,8446.9  ,182.6,191.7,200.8
XS GIS Cut Line= 3
     1829716.387      479715.777      1829951.63      479810.395
     1830057.533      479931.923
#Sta/Elev= 30
       0  790.06     9.8  785.81    19.5  780.74    29.3  775.26      39  769.35
    58.5  754.93    68.3  751.22      78  749.72    87.8  747.88    97.5  744.88
   107.3  742.65     117  743.14   126.8  745.65   136.5  747.67     156  747.49
   175.5  747.85   204.8  748.17   253.6  749.75   272.5  750.12     282  750.64
   291.5  752.34     301  754.66   310.4  757.91   329.4  766.52   338.9  771.17
   348.4  776.39   386.3  798.48   395.8  803.82   405.3  808.12   414.8  811.77
#Mann= 3 , 0 , 0
       0      .1       0    97.5    .045       0     117      .1       0
Bank Sta=97.5,117
XS Rating Curve= 0 ,0
Exp/Cntr=0.3,0.1

Type RM Length L Ch R = 1 ,8255.2  ,165,175.5,186
XS GIS Cut Line= 2
     1829592.568      479793.692     1829881.326      480078.744
#Sta/Elev= 30
       0  795.45     9.7  792.16    19.3  788.32    48.3  776.24    67.6  768.75
    77.3  765.18    96.6  758.53   115.9  748.91   135.2  744.12   144.9  741.13
   154.6  739.89   164.2   741.1   173.9  742.94   183.6  743.63   193.2   743.7
   202.9     744   212.5  744.15   222.2  744.01   241.5  744.05   299.5   743.5
   309.2  743.83   318.8  746.78   328.5  752.01   338.1  758.34   347.8  765.63
   367.1  785.26   376.8  793.43   386.4  800.96   396.1  807.82   405.8  812.87
#Mann= 3 , 0 , 0
       0      .1       0   144.9    .045       0   164.2      .1       0
#XS Ineff= 2 , 0
                          209.96          751.81
Permanent Ineff=
       F       F
Bank Sta=144.9,164.2
XS Rating Curve= 0 ,0
Exp/Cntr=0.3,0.1

Type RM Length L Ch R = 1 ,8079.7  ,173.9,166,158.1
XS GIS Cut Line= 4
     1829487.933      479865.934     1829549.817      479960.834
      1829584.77       480063.57     1829704.056      480203.544
#Sta/Elev= 30
       0  813.92    18.9  803.35    28.3   797.6    56.6  780.88    66.1  775.13
    75.5  769.74      85   765.3   113.3  753.46   122.3   749.4   131.4  745.12
   140.4  740.69   149.5  737.75   155.6  737.06   158.5  736.73   167.6  736.95
   170.6  737.43   176.6   738.4   185.6  740.38   194.7  740.86   241.2  741.38
   279.9   741.3   308.9  741.46   318.6  741.64   328.3  742.13     338  742.88
   347.6  745.36   376.7  762.61   386.4  769.85     396  777.87   405.7  785.39
#Mann= 3 , 0 , 0
       0      .1       0   155.6    .045       0   170.6      .1       0
Bank Sta=155.6,170.6
XS Rating Curve= 0 ,0
Exp/Cntr=0.3,0.1

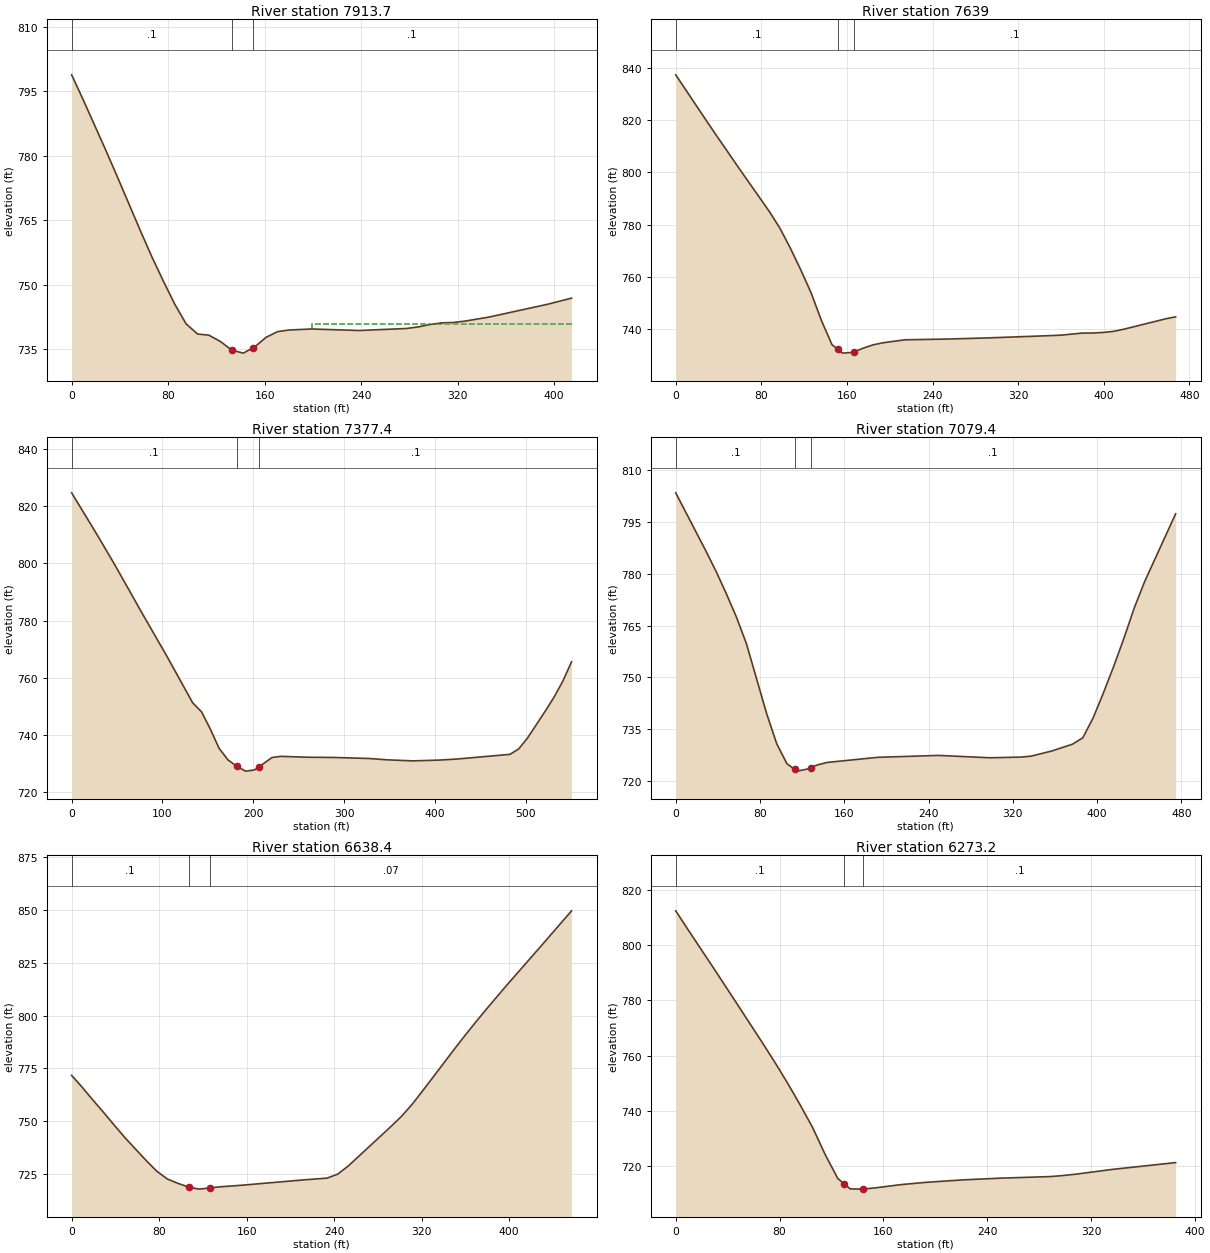
Type RM Length L Ch R = 1 ,7913.7  ,275.3,274.7,273.8
XS GIS Cut Line= 3
     1829325.326      479946.862     1829448.937      480103.112
     1829554.768      480290.434
#Sta/Elev= 30
       0  798.78     9.5  793.02    28.5  781.12      38  774.98    56.9  762.57
    66.4  756.52    75.9  750.87    85.4  745.48    94.9  740.86   104.4   738.5
   113.8  738.23   123.3  736.77   132.8  734.75   142.3  734.06   150.1  735.26
   151.8  735.52   161.3  737.76   170.8  739.07   180.3  739.44   199.2  739.67
   238.4  739.32   277.5  739.79   287.2  740.15     297  740.71   306.8  741.09
   316.6  741.19   326.4  741.52   345.9  742.44   394.8  745.44   414.4  746.85
#Mann= 3 , 0 , 0
       0      .1       0   132.8    .045       0   150.1      .1       0
#XS Ineff= 2 , 0
                           199.6          740.87
Permanent Ineff=
       F       F
Bank Sta=132.8,150.1
XS Rating Curve= 0 ,0
Exp/Cntr=0.3,0.1

Type RM Length L Ch R = 1 ,7639    ,261.4,261.6,261.8
XS GIS Cut Line= 2
     1829104.332      480073.642     1829405.878      480430.358
#Sta/Elev= 30
       0  837.45    29.2  819.53    38.9  813.68    58.4  802.04    87.6  784.95
    97.3  778.65     107  771.06   116.8  762.69   126.5  753.82   136.2  743.14
     146  733.95   151.3  732.17   155.7  730.69   165.4  730.95   166.3   731.1
   175.2   732.6   184.9  733.92   194.6  734.72   214.1   735.8     253  736.08
   291.9  736.53   350.3  737.41     360  737.58   379.5  738.37   389.2   738.4
     399  738.61   408.7  739.01   418.4  739.83   457.4  743.81   467.1  744.61
#Mann= 3 , 0 , 0
       0      .1       0   151.3    .045       0   166.3      .1       0
Bank Sta=151.3,166.3
XS Rating Curve= 0 ,0
Exp/Cntr=0.3,0.1

Type RM Length L Ch R = 1 ,7377.4  ,303.3,298.1,292.9
XS GIS Cut Line= 3
      1828948.51      480172.086     1828960.229      480304.898
     1829225.854      480626.513
#Sta/Elev= 30
       0  824.76    28.6  809.76    47.6  799.48    76.2  783.34   104.8  767.53
   133.3  751.15     143  748.02   152.7  741.95   162.4  735.19   172.1  731.18
   181.8  728.91   191.5  727.23   201.2  727.63   206.5  728.79   220.6     732
   230.3  732.41   259.4   732.1   288.5  732.02   327.3  731.66   346.7   731.2
   375.8  730.82   404.9   731.1   424.4  731.47   482.6  733.11   492.2  735.02
     502  738.87   521.4  748.23     531  753.08   540.8  758.77   550.4  765.55
#Mann= 3 , 0 , 0
       0      .1       0   181.8    .045       0   206.5      .1       0
Bank Sta=181.8,206.5
XS Rating Curve= 0 ,0
Exp/Cntr=0.3,0.1

Type RM Length L Ch R = 1 ,7079.4  ,446.2,441,435.5
XS GIS Cut Line= 3
     1828707.625       480502.26     1828906.236      480652.954
     1829051.375      480825.176
#Sta/Elev= 30
       0  803.44    28.8   786.5    38.4  780.63    47.9   774.3    57.5  767.52
    67.1  759.75    86.3  739.49    95.9  730.72   105.5  724.99     113  723.29
   115.1  722.81   124.6  723.39     128  723.81   134.2  724.58   143.8  725.33
   191.8  726.81   249.3  727.36   298.3  726.68   327.6  726.87   337.4  727.15
     357  728.65   376.6  730.61   386.4  732.46   396.2  738.22     406   745.5
   415.8  753.21   425.6  761.45   435.4  770.22   445.2  777.79   474.5  797.36
#Mann= 3 , 0 , 0
       0      .1       0     113    .045       0     128      .1       0
Bank Sta=113,128
XS Rating Curve= 0 ,0
Exp/Cntr=0.3,0.1

Type RM Length L Ch R = 1 ,6638.4  ,353.3,365.2,377
XS GIS Cut Line= 2
     1828594.458      480940.462     1829012.512      481125.173
#Sta/Elev= 30
       0  771.71     9.7  766.07    19.4  760.05    29.2  754.17    38.9  748.17
    48.6  742.29    68.1  731.41    77.8  726.35    87.5  722.64    97.2  720.58
     107  718.82   116.7  717.85   126.4  718.42   136.1  718.96   155.6   719.7
   213.9   722.3   233.4  723.05   243.1  724.91   252.8  728.78   291.7  747.42
   301.4  752.25   311.2  757.98   320.9  764.41   350.1  784.31   359.8  790.75
   369.5  797.01   379.2  803.11   398.7  814.99   427.9  832.24     457  849.65
#Mann= 3 , 0 , 0
       0      .1       0     107    .045       0   126.4     .07       0
Bank Sta=107,126.4
XS Rating Curve= 0 ,0
Exp/Cntr=0.3,0.1

Type RM Length L Ch R = 1 ,6273.2  ,238.4,240.8,242.8
XS GIS Cut Line= 3
      1828381.39      481181.038     1828458.473      481237.982
     1828629.306      481471.315
#Sta/Elev= 25
       0  812.44     9.6  805.54    28.8  791.96    47.9  778.26    67.1  764.41
    76.7  757.33    86.2     750    95.8  742.19   105.5  733.91   115.1  724.18
   124.8  715.52   129.5  713.66   134.4  711.73     144  711.65   144.5  711.67
   153.7  712.11     173  713.26   192.2  714.09   221.2     715   250.1  715.62
   288.6   716.2   298.3  716.57   307.9  717.05   336.8  718.82     385  721.26
#Mann= 3 , 0 , 0
       0      .1       0   129.5    .045       0   144.5      .1       0
Bank Sta=129.5,144.5
XS Rating Curve= 0 ,0
Exp/Cntr=0.3,0.1