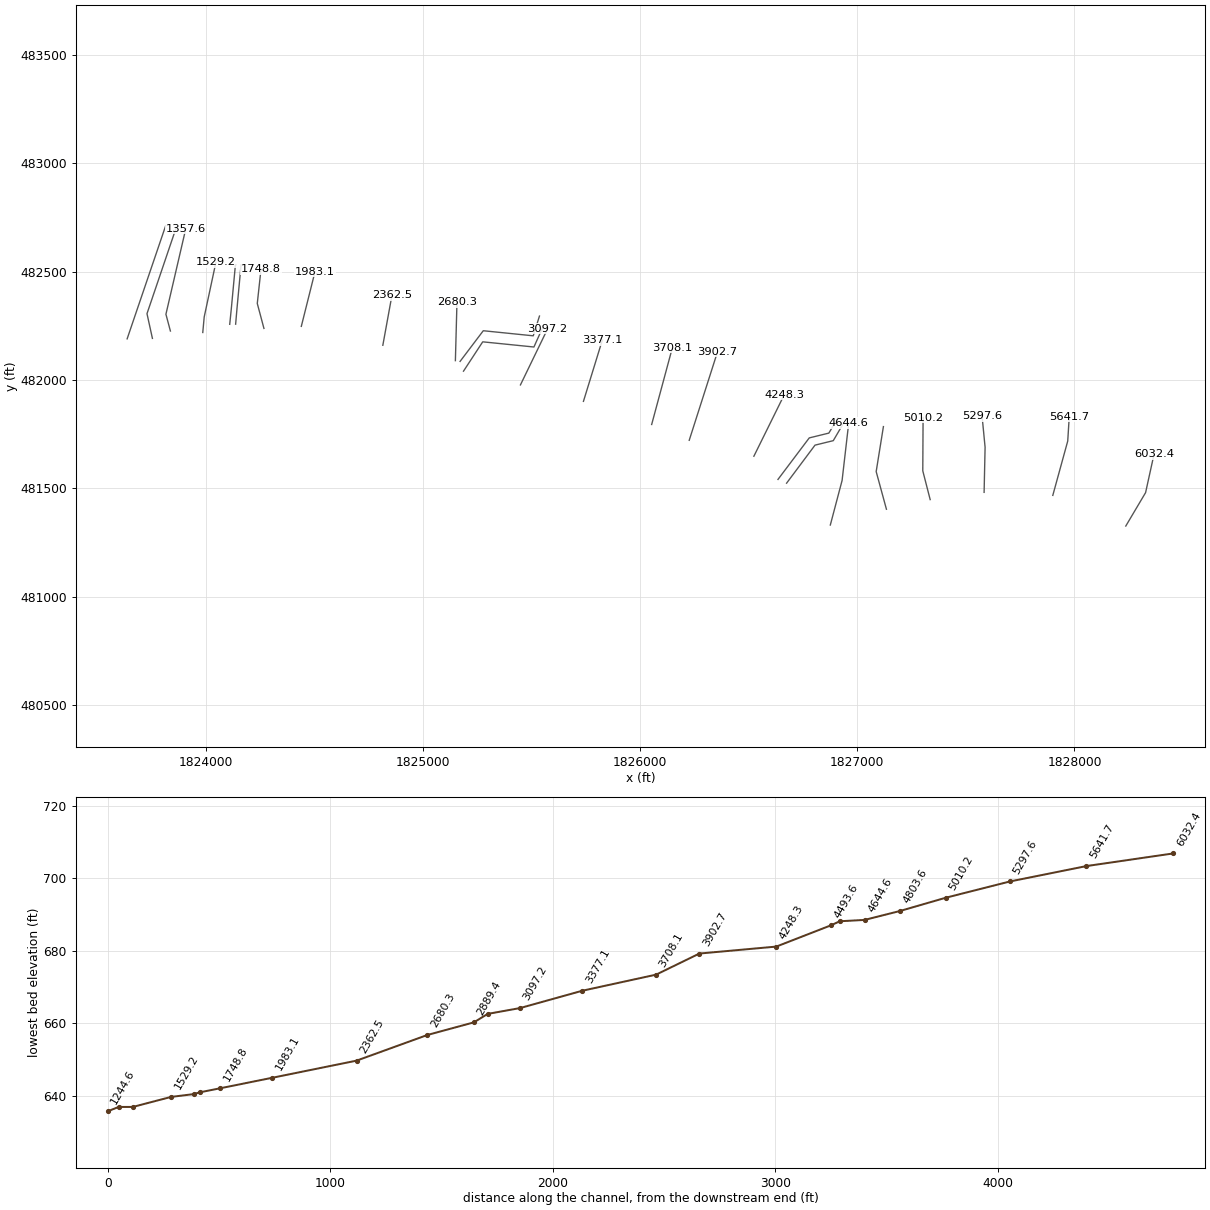
HEC-RAS study PTLCKFK.prj: PTLCKFK

--- PTLCKFK.g01 (geometry) --- (continued)

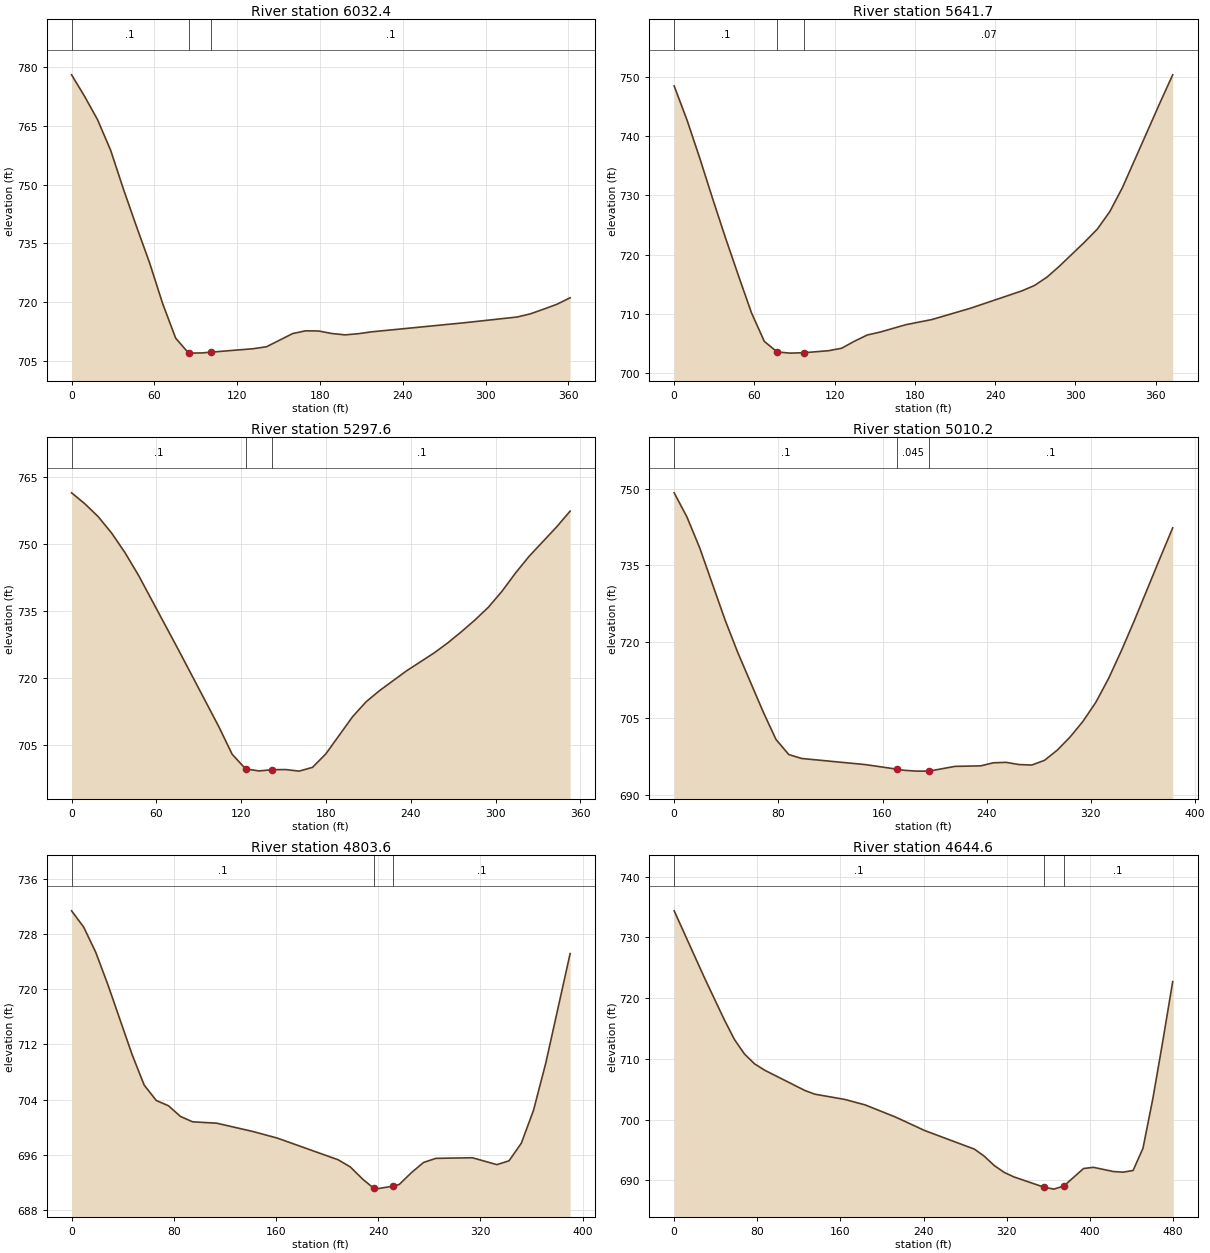
Type RM Length L Ch R = 1 ,6032.4  ,384.7,390.7,396.7
XS GIS Cut Line= 3
     1828236.164      481325.699      1828327.31      481479.779
     1828366.372       481657.73
#Sta/Elev= 27
       0  778.11     9.4  772.62    18.8  766.64    28.3   758.8    37.7  748.72
    47.1  739.22    56.5  730.01      66  719.54    75.4  710.73    84.8  706.89
    94.2  706.94   101.2  707.14   131.9  708.03   141.3  708.53   160.2   711.9
   169.6   712.6     179  712.55   188.6  711.91   198.2  711.56   207.8  711.86
   217.4  712.34   284.5  714.66   322.8  716.13   332.4  716.94     342  718.14
   351.6  719.39   361.2  721.05
#Mann= 3 , 0 , 0
       0      .1       0    84.8    .045       0   101.2      .1       0
Bank Sta=84.8,101.2
XS Rating Curve= 0 ,0
Exp/Cntr=0.3,0.1

Type RM Length L Ch R = 1 ,5641.7  ,338.6,344.1,349.7
XS GIS Cut Line= 3
      1827900.14      481467.149      1827968.89      481717.843
     1827975.834      481830.343
#Sta/Elev= 29
       0  748.46     9.6  742.71    19.3  736.17    28.9  729.35    38.5  722.75
    48.1  716.44    57.8   710.2    67.4  705.38      77   703.6    86.6   703.4
    97.1  703.47   115.5  703.81   125.2  704.22   134.8  705.41   144.4  706.46
     154  706.95   173.3   708.2   192.6  709.06   221.4  710.96     260   713.9
   269.3   714.8   278.7  716.21   288.1  718.08   306.9  722.14   316.3   724.3
   325.7  727.27   335.1   731.3   363.3  745.67   372.7  750.33
#Mann= 3 , 0 , 0
       0      .1       0      77    .045       0    97.1     .07       0
Bank Sta=77,97.1
XS Rating Curve= 0 ,0
Exp/Cntr=0.3,0.1

Type RM Length L Ch R = 1 ,5297.6  ,287,287.4,287.7
XS GIS Cut Line= 3
     1827583.876      481481.052     1827588.386      481689.355
     1827574.445      481833.121
#Sta/Elev= 30
       0  761.41     9.5  758.93    18.9  756.06    28.4  752.38    37.9  747.97
    47.4  742.94    75.8  726.18   104.2  709.09   113.6  702.94   123.1  699.66
   132.6  699.19   142.1  699.47   151.5   699.5     161  699.15   170.5  699.99
   179.9     703   198.9  711.34   208.4  714.66     218  717.18   237.2  721.62
   256.5  725.58   266.1  727.81   275.8  730.32   285.4  732.95     295  735.83
   304.6  739.39   314.3  743.53   323.9  747.25   343.2  753.77   352.8  757.32
#Mann= 3 , 0 , 0
       0      .1       0   123.1    .045       0   142.1      .1       0
Bank Sta=123.1,142.1
XS Rating Curve= 0 ,0
Exp/Cntr=0.3,0.1

Type RM Length L Ch R = 1 ,5010.2  ,210,206.6,203.1
XS GIS Cut Line= 3
     1827335.556      481447.704     1827301.529      481580.343
     1827302.917      481826.177
#Sta/Elev= 30
       0  749.19     9.8  744.47    19.6  738.42    39.1  724.28    48.9  717.88
    68.5   706.2    78.2  700.88      88  697.93    97.8  697.16   146.8  695.96
   170.8  695.07   176.3  694.85   186.1  694.68   195.9  694.69   215.6  695.61
   235.3  695.71   245.1  696.31   254.9   696.4   264.8  695.97   274.6  695.87
   284.4   696.8   294.3  698.82   304.1  701.39   313.9  704.43   323.8  708.17
   333.6  712.84   343.4  718.27   353.3  724.14   372.9  736.29   382.8  742.33
#Mann= 3 , 0 , 0
       0      .1       0   170.8    .045       0   195.9      .1       0
Bank Sta=170.8,195.9
XS Rating Curve= 0 ,0
Exp/Cntr=0.3,0.1

Type RM Length L Ch R = 1 ,4803.6  ,158,159.1,160.1
XS GIS Cut Line= 3
     1827134.167       481403.26     1827086.945      481576.871
     1827120.279       481784.51
#Sta/Elev= 30
       0  731.36     9.5  728.99    18.9  725.35    28.4  720.66    47.4   710.5
    56.8   706.1    66.3  703.86    75.8   703.1    85.2  701.55    94.7  700.77
   113.6  700.57     142  699.36     161  698.41   208.6  695.27   218.2  694.22
   227.7  692.48   236.6  691.12   237.3  691.01   251.6  691.44   256.4  691.68
     266   693.4   275.5  694.88   285.1  695.47   313.7  695.56   332.9  694.56
   342.4  695.12     352  697.67   361.5  702.41   371.1  709.25   390.2  725.16
#Mann= 3 , 0 , 0
       0      .1       0   236.6    .045       0   251.6      .1       0
Bank Sta=236.6,251.6
XS Rating Curve= 0 ,0
Exp/Cntr=0.3,0.1

Type RM Length L Ch R = 1 ,4644.6  ,140.2,111.3,81
XS GIS Cut Line= 3
     1826875.834      481330.343     1826930.001      481535.899
     1826960.556      481801.177
#Sta/Elev= 30
       0  734.36      29  723.39    48.3  716.41      58  713.18    67.6   710.8
    77.3  709.18      87  708.13   125.6   704.8   135.3  704.18   164.3  703.31
   183.6  702.42   212.6  700.44   241.2  698.18   288.9  695.13   298.4  693.96
   307.9  692.44   317.5   691.3     327  690.55   355.6  688.88   365.2  688.55
   374.8  689.05   393.8  691.94   403.3  692.14   422.4  691.45   431.9  691.34
   441.5  691.62     451  695.27   460.5  703.44   470.1  712.93   479.6   722.7
#Mann= 3 , 0 , 0
       0      .1       0   355.6    .045       0   374.8      .1       0
Bank Sta=355.6,374.8
XS Rating Curve= 0 ,0
Exp/Cntr=0.3,0.1

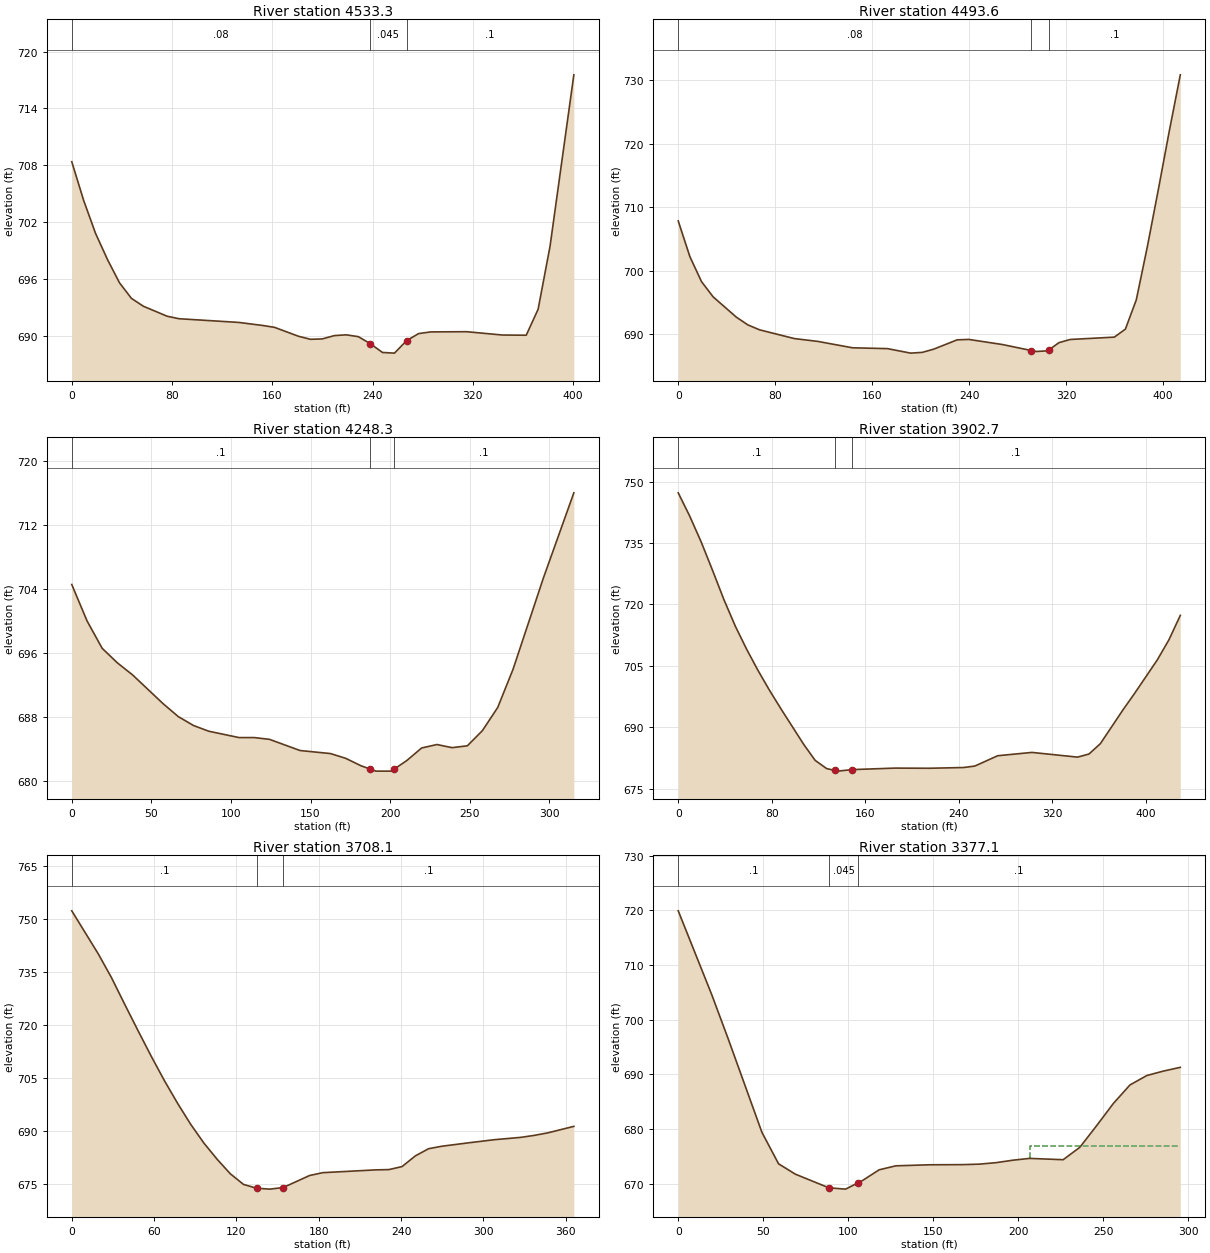
Type RM Length L Ch R = 1 ,4533.3  ,44.2,39.7,39.8
XS GIS Cut Line= 4
     1826674.445      481523.399     1826805.371      481698.928
     1826889.506      481719.638     1826937.361      481801.623
#Sta/Elev= 30
       0  708.38     9.5  704.29      19  700.81    28.6  698.03    38.1   695.6
    47.6  693.96    57.1  693.13    76.2  692.07    85.7  691.81   133.3  691.42
   152.3   691.1   161.8   690.9   180.9  689.96   190.4  689.64   199.9  689.68
   209.5  690.03     219  690.11   228.6  689.92   238.2  689.18   247.9  688.25
   257.5  688.18   267.1  689.49   276.7  690.24   286.4  690.42   315.1  690.44
   343.6  690.09   362.6  690.07   372.1  692.81   381.6  699.45   400.6  717.55
#Mann= 3 , 0 , 0
       0     .08       0   238.2    .045       0   267.1      .1       0
Bank Sta=238.2,267.1
XS Rating Curve= 0 ,0
Exp/Cntr=0.3,0.1

Type RM Length L Ch R = 1 ,4493.6  ,220.5,245.3,266.3
XS GIS Cut Line= 4
     1826634.862       481540.76     1826778.818      481732.285
     1826869.103      481754.509     1826910.652      481824.623
#Sta/Elev= 30
       0  707.88     9.6  702.26    19.2  698.32    28.8  695.92    47.9  692.73
    57.5   691.5    67.1  690.73    95.8  689.35     115  688.91   143.8   687.9
   172.5  687.77   191.7  687.06   201.3  687.18   210.8  687.69     230  689.15
   239.6  689.22   267.5  688.41   291.2  687.47   295.4  687.32   304.7  687.42
   306.2  687.63     314  688.71   323.3  689.21   359.7  689.58   368.8  690.84
   377.8  695.45   386.9  703.81     396  712.84     405  722.02   414.1  730.89
#Mann= 3 , 0 , 0
       0     .08       0   291.2    .045       0   306.2      .1       0
Bank Sta=291.2,306.2
XS Rating Curve= 0 ,0
Exp/Cntr=0.3,0.1

Type RM Length L Ch R = 1 ,4248.3  ,342,345.6,349
XS GIS Cut Line= 2
     1826523.918      481647.771     1826663.345      481930.667
#Sta/Elev= 30
       0  704.57     9.6  700.01    19.1  696.58    28.7  694.75    38.2  693.25
    57.3  689.66    66.9  688.03    76.5  686.91      86   686.2   105.1   685.4
   114.7   685.4   124.2  685.18   143.4  683.78   162.5   683.4     172  682.81
   181.6  681.88   187.6  681.45   191.1   681.2   200.7   681.2   202.6  681.46
   210.3   682.5   219.8   684.1   229.4  684.53   238.9  684.14   248.5  684.37
     258  686.28   267.6  689.18   277.2  693.95   296.3   705.4   315.4  716.05
#Mann= 3 , 0 , 0
       0      .1       0   187.6    .045       0   202.6      .1       0
Bank Sta=187.6,202.6
XS Rating Curve= 0 ,0
Exp/Cntr=0.3,0.1

Type RM Length L Ch R = 1 ,3902.7  ,193.6,194.7,195.7
XS GIS Cut Line= 2
      1826226.21      481721.315     1826356.765      482130.343
#Sta/Elev= 30
       0  747.26     9.8  741.59    19.5  735.35    29.3  728.36      39  721.23
    48.8   714.7    58.6     709    68.3  703.84    78.1     699    87.8  694.52
   107.3  685.82   117.1  681.91   126.9   679.9   133.7  679.47   136.6  679.28
   148.7  679.65   185.4  680.02   214.7  679.98     244  680.16   253.7  680.52
   273.2  683.04   302.5  683.85   341.5   682.7   351.3  683.46     361  685.98
   380.6  694.34   390.3  698.26   409.8  706.49   419.6  711.32   429.4  717.32
#Mann= 3 , 0 , 0
       0      .1       0   133.7    .045       0   148.7      .1       0
Bank Sta=133.7,148.7
XS Rating Curve= 0 ,0
Exp/Cntr=0.3,0.1

Type RM Length L Ch R = 1 ,3708.1  ,331.7,331,330.1
XS GIS Cut Line= 2
     1826053.293      481794.232     1826148.432      482147.704
#Sta/Elev= 30
       0  752.25    19.3  740.08    28.9  733.37    38.5  725.86    48.2  718.41
    57.8  711.17    67.4  704.27    77.1  697.78    86.7  691.81    96.3  686.51
     106   681.9   115.6   677.8   125.2  674.79   134.9   673.7   144.5  673.46
   154.1  673.91   173.4  677.32     183  678.12   221.6  678.91   231.2  678.99
   240.8  679.85   250.5  682.88   260.1   684.9   269.7   685.6     289  686.56
   308.2  687.46   327.5  688.12   337.2  688.68   346.8  689.37     366  691.23
#Mann= 3 , 0 , 0
       0      .1       0   134.9    .045       0   154.1      .1       0
Bank Sta=134.9,154.1
XS Rating Curve= 0 ,0
Exp/Cntr=0.3,0.1

Type RM Length L Ch R = 1 ,3377.1  ,283.3,279.9,276.5
XS GIS Cut Line= 2
     1825739.231      481901.003     1825826.036      482183.121
#Sta/Elev= 26
       0  719.92    19.7  704.59    29.5  696.41    49.2  679.42      59  673.66
    68.9  671.76    88.6  669.27    98.4  669.03   105.7  670.18   108.2  670.57
   118.1  672.56   127.9  673.29   147.6  673.48   167.3  673.51   177.1   673.6
   186.9  673.87   196.8  674.32   206.6  674.65   226.3  674.41   236.1  676.67
     246  680.63   255.8  684.68   265.6  688.08   275.5   689.8   285.3  690.62
   295.2   691.3
#Mann= 3 , 0 , 0
       0      .1       0    88.6    .045       0   105.7      .1       0
#XS Ineff= 2 , 0
                          206.73             677
Permanent Ineff=
       F       F
Bank Sta=88.6,105.7
XS Rating Curve= 0 ,0
Exp/Cntr=0.3,0.1

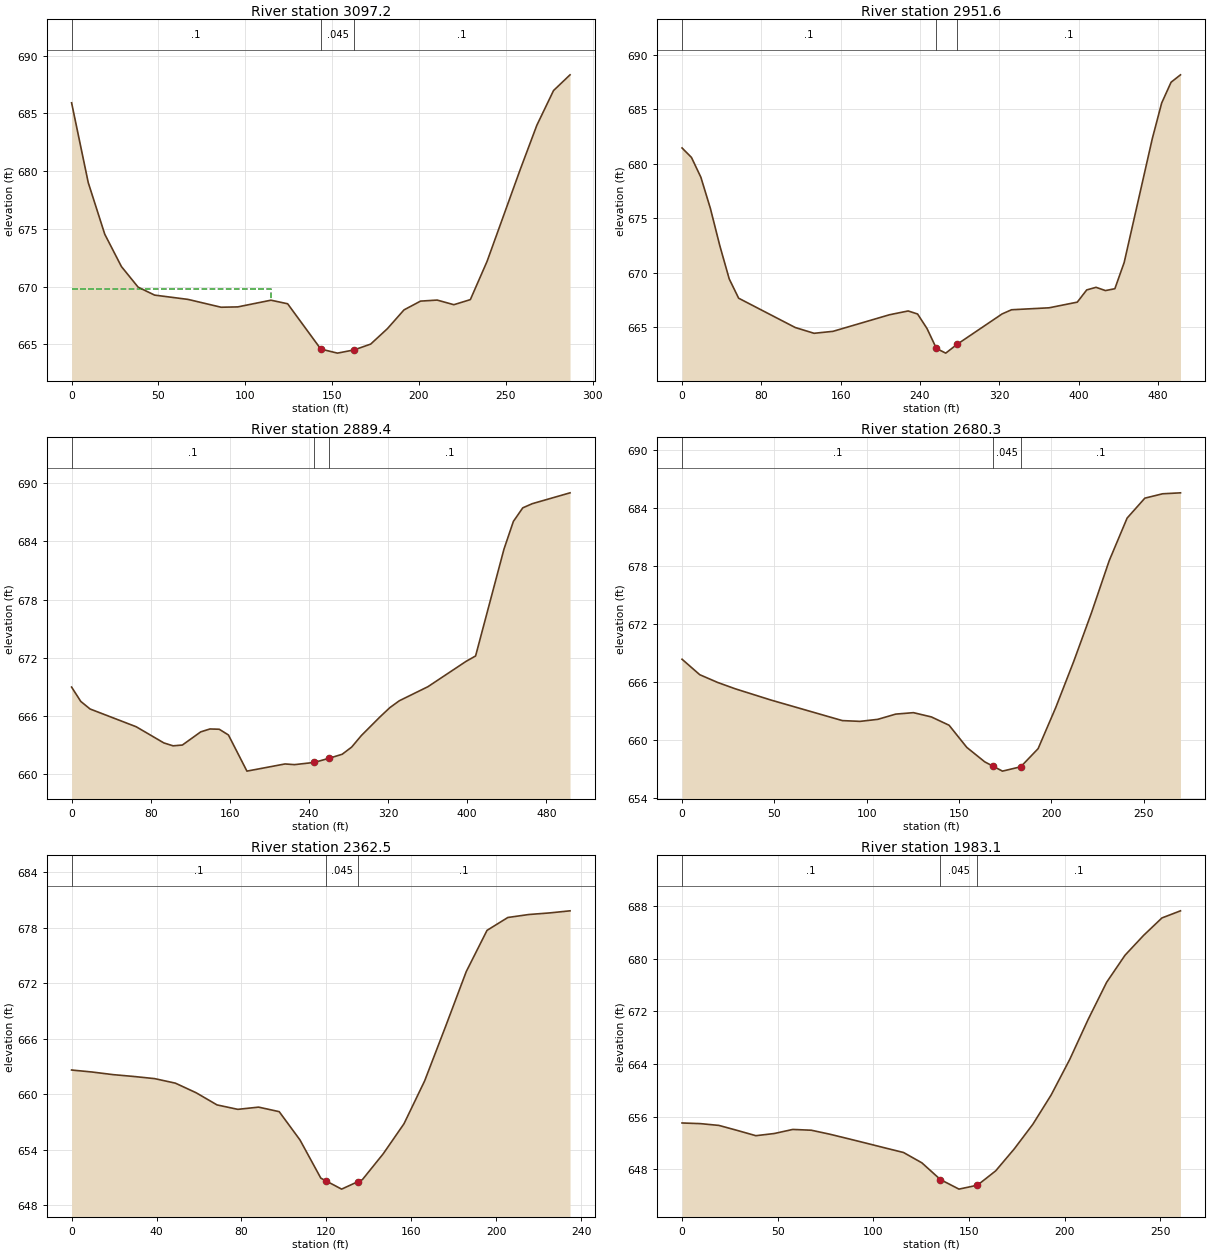
Type RM Length L Ch R = 1 ,3097.2  ,175.7,145.6,96.7
XS GIS Cut Line= 2
     1825449.155      481976.784     1825574.051      482235.228
#Sta/Elev= 26
       0  685.91     9.6     679    19.1  674.54    28.7  671.74    38.3  669.96
    47.8  669.27      67   668.9    86.1  668.22    95.7  668.25   114.8  668.83
   124.4  668.52   143.5   664.6   153.1  664.25   162.7  664.53   172.2  665.03
   181.8  666.36   191.4  667.99   200.9  668.75   210.5  668.84   220.1  668.44
   229.6  668.88   239.2  672.18   258.3  680.13   267.9  683.97   277.5  686.97
     287  688.33
#Mann= 3 , 0 , 0
       0      .1       0   143.5    .045       0   162.7      .1       0
#XS Ineff= 2 , 0
          114.63  669.76
Permanent Ineff=
       F       F
Bank Sta=143.5,162.7
XS Rating Curve= 0 ,0
Exp/Cntr=0.3,0.1

Type RM Length L Ch R = 1 ,2951.6  ,105.5,62.2,81.5
XS GIS Cut Line= 4
     1825186.918      482040.138      1825275.46      482175.555
     1825511.187       482151.71       1825553.8      482246.607
#Sta/Elev= 30
       0  681.47     9.5   680.6      19  678.78    28.6  675.92    38.1   672.5
    47.6  669.45    57.1  667.68   114.2  664.99   133.2  664.46   152.3  664.64
   209.2  666.16   228.1  666.51   237.6  666.23   247.1   664.9   256.6  663.07
     266  662.64   277.5  663.45   322.9  666.24   332.4  666.62   370.3   666.8
   398.7  667.32   408.2  668.44   417.6  668.68   427.1  668.38   436.6  668.55
     446  670.96   474.4  682.34   483.8  685.59   493.3   687.5   502.8  688.18
#Mann= 3 , 0 , 0
       0      .1       0   256.6    .045       0   277.5      .1       0
Bank Sta=256.6,277.5
XS Rating Curve= 0 ,0
Exp/Cntr=0.3,0.1

Type RM Length L Ch R = 1 ,2889.4  ,125.4,209.1,248
XS GIS Cut Line= 4
     1825171.293      482085.277     1825278.064       482226.77
     1825508.099      482203.332     1825536.745      482294.478
#Sta/Elev= 30
       0  668.97     9.3  667.49    18.7  666.71    65.3  664.88    93.3  663.21
   102.6  662.91     112  662.99   130.6  664.35   139.9  664.65   149.3  664.62
   158.6  664.03   177.3   660.3   215.8  661.04   225.4  660.97   245.5   661.2
   260.5  661.63   273.6  662.04   283.2  662.78   292.9  663.96   312.1  665.92
   321.8  666.85   331.4  667.56   360.3  669.01   398.8  671.62   408.5  672.18
   437.2   683.2   446.7  686.06   456.2  687.46   465.8  687.89     504  689.01
#Mann= 3 , 0 , 0
       0      .1       0   245.5    .045       0   260.5      .1       0
Bank Sta=245.5,260.5
XS Rating Curve= 0 ,0
Exp/Cntr=0.3,0.1

Type RM Length L Ch R = 1 ,2680.3  ,321.1,317.8,314.2
XS GIS Cut Line= 2
     1825149.634      482088.795     1825156.925      482358.587
#Sta/Elev= 26
       0  668.38     9.6  666.78    19.3  665.98    28.9  665.32    48.2  664.16
    86.8  662.04    96.4  661.96     106  662.17   115.7  662.71   125.3  662.86
     135  662.42   144.6  661.56   154.2  659.27   163.9  657.78   168.4  657.33
   173.5  656.82   183.4  657.27   192.8  659.14   202.4  663.41   212.1  668.16
   221.7  673.18   231.3  678.56     241  682.96   250.6  685.02   260.2  685.47
   269.9  685.57
#Mann= 3 , 0 , 0
       0      .1       0   168.4    .045       0   183.4      .1       0
Bank Sta=168.4,183.4
XS Rating Curve= 0 ,0
Exp/Cntr=0.3,0.1

Type RM Length L Ch R = 1 ,2362.5  ,380.8,379.4,377.7
XS GIS Cut Line= 2
      1824815.62      482159.683     1824857.663      482390.726
#Sta/Elev= 27
       0  662.62     9.8   662.4    19.6  662.12    29.4  661.92    39.1  661.69
    48.9   661.2    58.7  660.16    68.5  658.85    78.3  658.37    88.1  658.61
    97.8  658.12   107.6  655.06   117.4  650.94     120  650.62   127.2  649.75
     135  650.57     137  650.78   146.8  653.57   156.6  656.82   166.3  661.44
   176.1  667.28   185.9  673.25   195.7  677.71   205.5   679.1   215.3  679.42
     225  679.59   234.8  679.82
#Mann= 3 , 0 , 0
       0      .1       0     120    .045       0     135      .1       0
Bank Sta=120,135
XS Rating Curve= 0 ,0
Exp/Cntr=0.3,0.1

Type RM Length L Ch R = 1 ,1983.1  ,231.1,234.2,237.3
XS GIS Cut Line= 2
     1824440.302      482246.976     1824503.496      482499.754
#Sta/Elev= 30
       0  655.06     9.6  654.96    19.3  654.69      29  653.92    38.6  653.13
    48.2  653.46    57.9  654.08    67.6  653.96    77.2  653.36    86.8  652.68
    96.5  651.98   106.2  651.27   115.8  650.58   125.4  649.01   135.1  646.47
   144.8  645.02   144.9  645.03   154.4  645.61   159.9  646.86     164   647.8
   173.7  651.13   183.4  654.86     193  659.32   202.7  664.71   212.3  670.76
     222  676.42   231.6  680.52   241.3  683.53   250.9  686.18   260.6  687.26
#Mann= 3 , 0 , 0
       0      .1       0   135.1    .045       0   154.4      .1       0
Bank Sta=135.1,154.4
XS Rating Curve= 0 ,0
Exp/Cntr=0.3,0.1

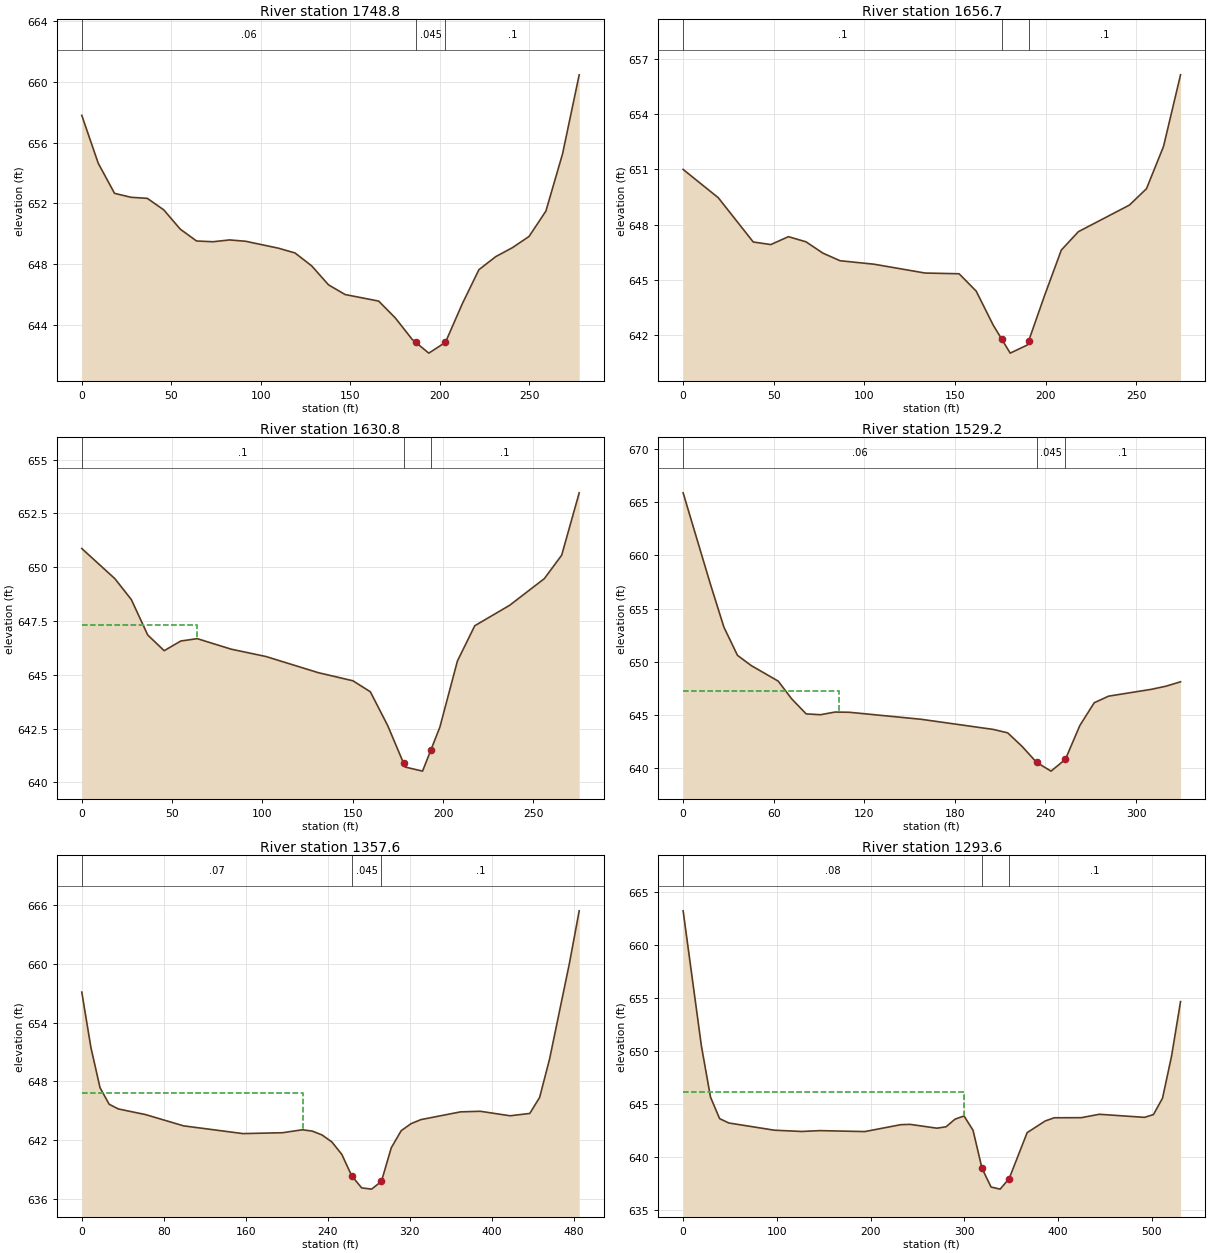
Type RM Length L Ch R = 1 ,1748.8  ,91.8,92.1,92.4
XS GIS Cut Line= 3
      1824268.19      482237.504     1824237.547      482352.612
     1824254.696      482510.391
#Sta/Elev= 30
       0  657.79     9.2  654.63    18.3  652.65    27.5  652.39    36.6  652.32
    45.8  651.56      55  650.29    64.1  649.51    73.3  649.46    82.5  649.58
    91.6  649.49     110  649.03   119.1  648.72   128.4  647.87   137.8  646.62
   147.1  645.98   165.8  645.55   175.1  644.44   184.5  643.03   186.4  642.84
   193.8  642.12   203.1  642.83   212.5  645.37   221.8  647.62   231.2  648.48
   240.5  649.07   249.8  649.81   259.2  651.48   268.5  655.25   277.8  660.46
#Mann= 3 , 0 , 0
       0     .06       0   186.4    .045       0   203.1      .1       0
Bank Sta=186.4,203.1
XS Rating Curve= 0 ,0
Exp/Cntr=0.3,0.1

Type RM Length L Ch R = 1 ,1656.7  ,26,26,26
XS GIS Cut Line= 3
     1824137.936      482257.066     1824143.711      482324.566
     1824162.895      482530.467
#Sta/Elev= 24
       0     651    19.4  649.46    38.7  647.05    48.4  646.91    58.1  647.34
    67.8  647.06    77.2  646.44    86.6  646.03   105.4  645.84   133.5  645.36
   152.3  645.32   161.7  644.38   171.1  642.53   175.7  641.78   180.5     641
   189.9  641.44   190.7  641.67   199.3  644.09   208.7  646.61   218.1  647.61
   246.3  649.06   255.7  649.95   265.1  652.25   274.5  656.15
#Mann= 3 , 0 , 0
       0      .1       0   175.7    .045       0   190.7      .1       0
Bank Sta=175.7,190.7
XS Rating Curve= 0 ,0
Exp/Cntr=0.3,0.1

Type RM Length L Ch R = 1 ,1630.8  ,104.2,101.6,98.8
XS GIS Cut Line= 3
     1824110.693      482256.447     1824118.093      482329.116
     1824136.853      482530.467
#Sta/Elev= 24
       0  650.87    18.3  649.47    27.4   648.5    36.5  646.85    45.6  646.12
    54.8  646.57    63.9  646.68    82.7  646.19   101.9  645.85   130.8   645.1
   150.1  644.72   159.7  644.21   169.3  642.64   178.1  640.89     179  640.71
   188.6  640.52   193.1  641.48   198.2  642.57   207.9  645.64   217.5  647.28
   236.8  648.23     256  649.47   265.6  650.56   275.3  653.46
#Mann= 3 , 0 , 0
       0      .1       0   178.1    .045       0   193.1      .1       0
#XS Ineff= 2 , 0
           63.95   647.3
Permanent Ineff=
       F       F
Bank Sta=178.1,193.1
XS Rating Curve= 0 ,0
Exp/Cntr=0.3,0.1

Type RM Length L Ch R = 1 ,1529.2  ,172,171.6,171.2
XS GIS Cut Line= 3
     1823986.635      482218.626     1823993.182       482290.27
     1824047.009      482542.186
#Sta/Elev= 24
       0  665.85      18  657.32      27  653.26      36  650.61      45  649.66
      63  648.19    71.9  646.53    81.5  645.12      91  645.04   100.6  645.29
   110.1  645.27   157.8  644.61   205.5  643.66     215  643.34   224.6  642.06
   234.1  640.58   243.7  639.75   253.2  640.85   262.8  644.03   272.3  646.16
   281.8  646.78   310.5  647.43     320  647.72   329.5  648.13
#Mann= 3 , 0 , 0
       0     .06       0   234.1    .045       0   253.2      .1       0
#XS Ineff= 2 , 0
          103.36  647.25
Permanent Ineff=
       F       F
Bank Sta=234.1,253.2
XS Rating Curve= 0 ,0
Exp/Cntr=0.3,0.1

Type RM Length L Ch R = 1 ,1357.6  ,66.1,63.9,61.6
XS GIS Cut Line= 3
     1823837.569      482225.421     1823816.963      482302.766
     1823908.448      482697.718
#Sta/Elev= 30
       0  657.11     8.9  651.46    17.8  647.35    26.7  645.66    35.6  645.18
    62.3   644.6    99.4  643.45   157.3  642.66   195.9  642.75   215.2  643.05
   224.8  642.92   234.5  642.52   244.1   641.8   253.8  640.53   263.4  638.35
   273.1  637.12   282.8  636.99   292.4  637.78     302  641.21   311.7  642.96
   321.4  643.68     331  644.09   369.6  644.88   388.9  644.94   417.9  644.48
   437.2  644.72   446.8  646.36   456.5  650.28   475.8  660.02   485.4  665.41
#Mann= 3 , 0 , 0
       0     .07       0   263.4    .045       0   292.4      .1       0
#XS Ineff= 2 , 0
          215.65  646.78
Permanent Ineff=
       F       F
Bank Sta=263.4,292.4
XS Rating Curve= 0 ,0
Exp/Cntr=0.3,0.1

Type RM Length L Ch R = 1 ,1293.6  ,49,49.1,48.9
XS GIS Cut Line= 3
     1823754.754      482191.446     1823729.781      482305.522
      1823862.54      482697.375
#Sta/Elev= 30
       0  663.19    19.5  650.46    29.2  645.65    38.9  643.62    48.7  643.21
    97.3  642.53   126.4  642.41   145.6  642.49   193.8   642.4   232.2  643.05
   241.9  643.08   270.7  642.72   280.4  642.85     290  643.57   299.6  643.87
   309.2  642.52   318.8  638.93   328.4  637.18   338.1  636.98   347.7  637.97
   366.9   642.3   386.2   643.4   395.8   643.7   424.7  643.71   443.9  644.03
     492  643.74   501.6     644   511.3  645.55   520.9   649.5   530.5  654.64
#Mann= 3 , 0 , 0
       0     .08       0   318.8    .045       0   347.7      .1       0
#XS Ineff= 2 , 0
          299.15  646.15
Permanent Ineff=
       F       F
Bank Sta=318.8,347.7
XS Rating Curve= 0 ,0
Exp/Cntr=0.3,0.1

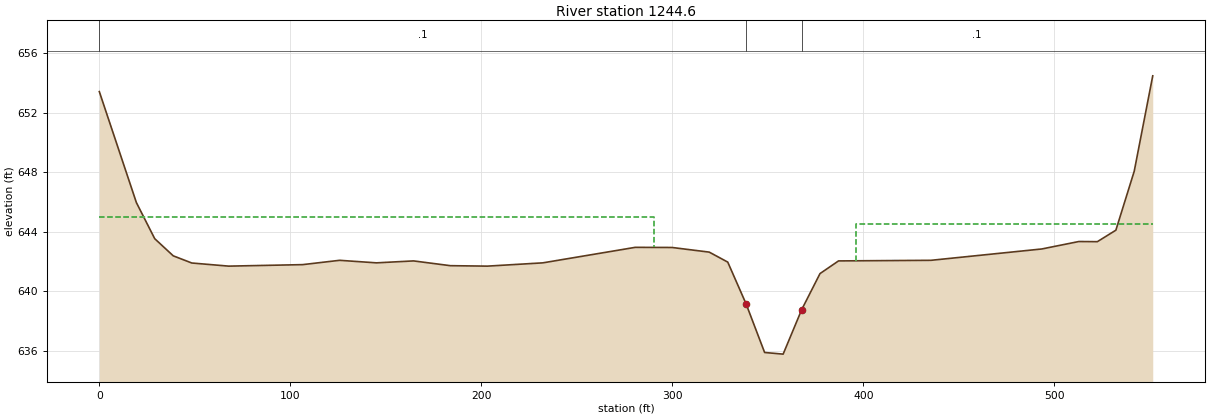
Type RM Length L Ch R = 1 ,1244.6  ,69.1,76.2,83.3
XS GIS Cut Line= 2
     1823638.389      482189.322     1823815.882      482711.481
#Sta/Elev= 30
       0   653.4    19.4  645.96      29  643.54    38.7  642.39    48.4  641.91
    67.7   641.7   106.4   641.8   125.8  642.09   145.1  641.92   164.5  642.05
   183.8  641.73   203.2   641.7   232.2  641.92   280.6  642.96   299.9  642.95
   319.3  642.64     329  641.97   338.6  639.17   348.3  635.91     358   635.8
   367.7  638.78   377.3   641.2     387  642.05   435.4  642.09   493.4  642.85
   512.8  643.35   522.5  643.34   532.2  644.11   541.8  648.06   551.5  654.46
#Mann= 3 , 0 , 0
       0      .1       0   338.6    .045       0   367.7      .1       0
#XS Ineff= 2 , 0
          290.23     645  396.03           644.5
Permanent Ineff=
       F       F
Bank Sta=338.6,367.7
XS Rating Curve= 0 ,0
Exp/Cntr=0.3,0.1