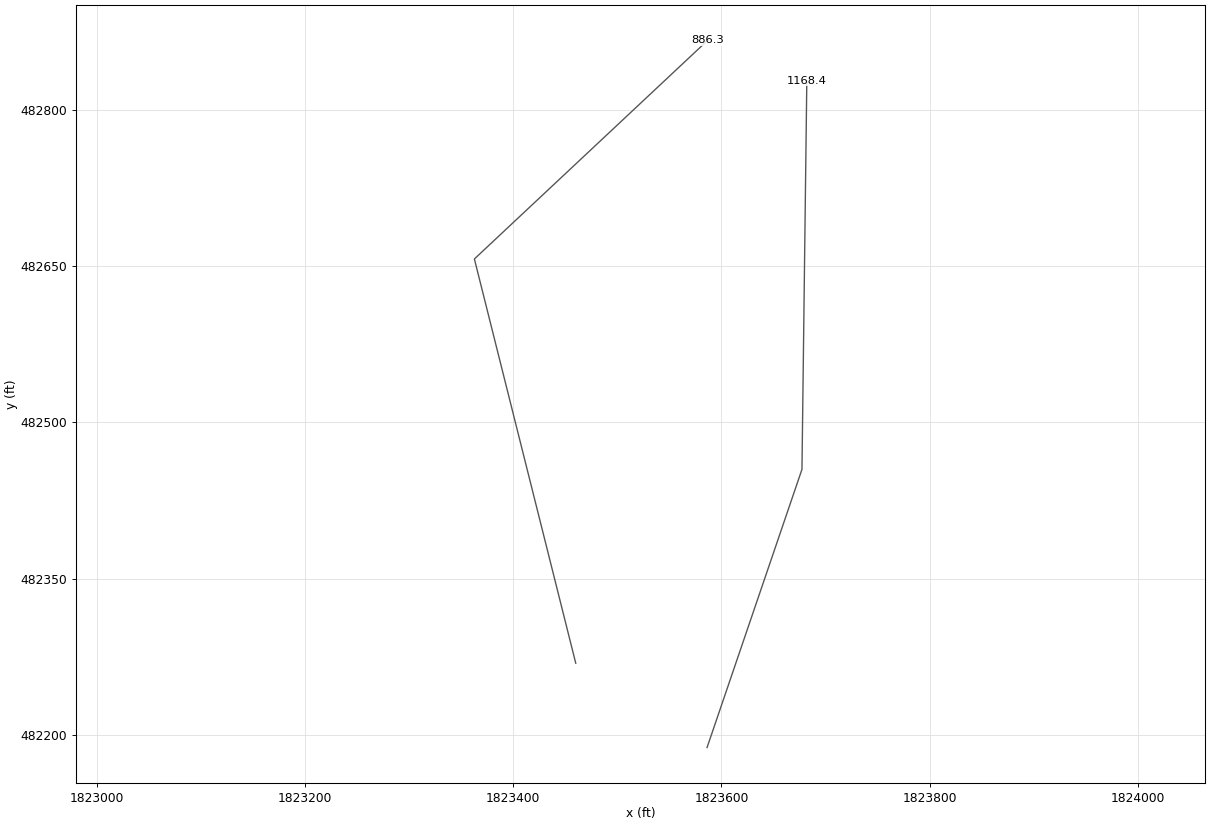
HEC-RAS study PTLCKFK.prj: PTLCKFK

--- PTLCKFK.g01 (geometry) --- (continued)

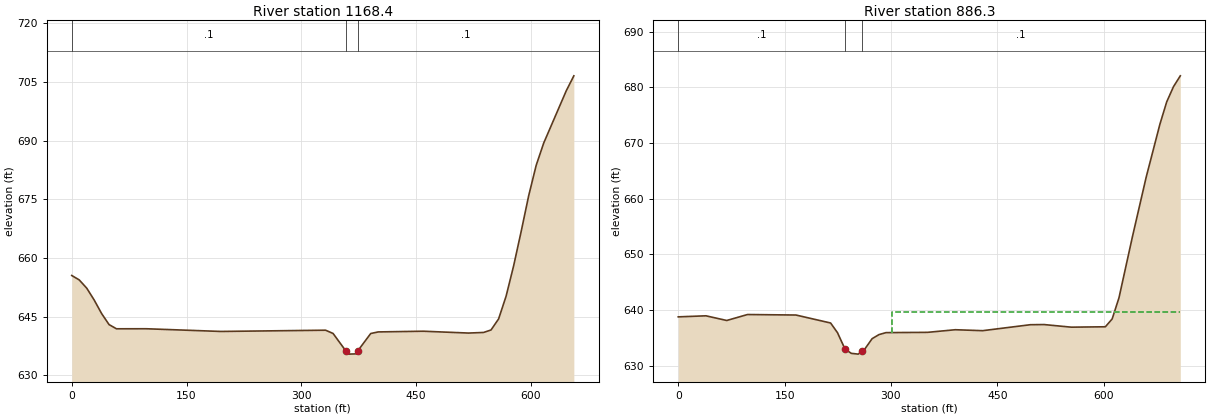
Type RM Length L Ch R = 1 ,1168.4  ,276.1,282,287.8
XS GIS Cut Line= 3
     1823586.152      482187.623     1823677.358      482454.961
     1823682.015       482828.42
#Sta/Elev= 30
       0  655.51     9.7  654.39    19.5  652.29    29.2  649.27      39  645.78
    48.7  642.96    58.4  641.88    97.4  641.89   194.8   641.2   331.6  641.52
   341.4  640.69   358.4  636.14   361.1   635.4   370.9  635.46   373.4  636.16
   390.6  640.67   400.4  641.08   459.4  641.26   518.4  640.79     538  640.94
   547.8  641.58   557.7  644.41   567.5  650.23   577.3  657.96   587.2   666.8
     597  675.92   606.8   683.7   616.6  689.38   646.1  702.77     656  706.59
#Mann= 3 , 0 , 0
       0      .1       0   358.4    .045       0   373.4      .1       0
Bank Sta=358.4,373.4
XS Rating Curve= 0 ,0
Exp/Cntr=0.3,0.1

Type RM Length L Ch R = 1 ,886.3   ,904,886.3,867.2
XS GIS Cut Line= 3
      1823460.01      482268.677     1823362.625      482657.078
     1823587.142      482867.486
#Sta/Elev= 30
       0  638.78    39.1  638.97    68.4  638.13    97.7   639.2     166  639.11
   214.9  637.68   224.6  635.94   235.3632.9739   244.1  632.23   253.9  632.09
   259.2632.6404   263.7  633.11   273.5  634.87   283.2   635.6     293  635.95
   351.6     636   390.7  636.47   429.3   636.3   496.6  637.37   515.8   637.4
   554.3  636.93   602.4     637     612  638.41   621.6   642.2   640.8   653.3
     660  663.88   679.3  673.36   688.9  677.38   698.5  680.12   708.1  682.06
#Mann= 3 , 0 , 0
       0      .1       0   235.3    .045       0   259.2      .1       0
#XS Ineff= 2 , 0
                          301.98           639.7
Permanent Ineff=
       F       F
Bank Sta=235.3,259.2
XS Rating Curve= 0 ,0
Exp/Cntr=0.3,0.1

Chan Stop Cuts=-1
Use User Specified Reach Order=0
Composite Channel Slope=5